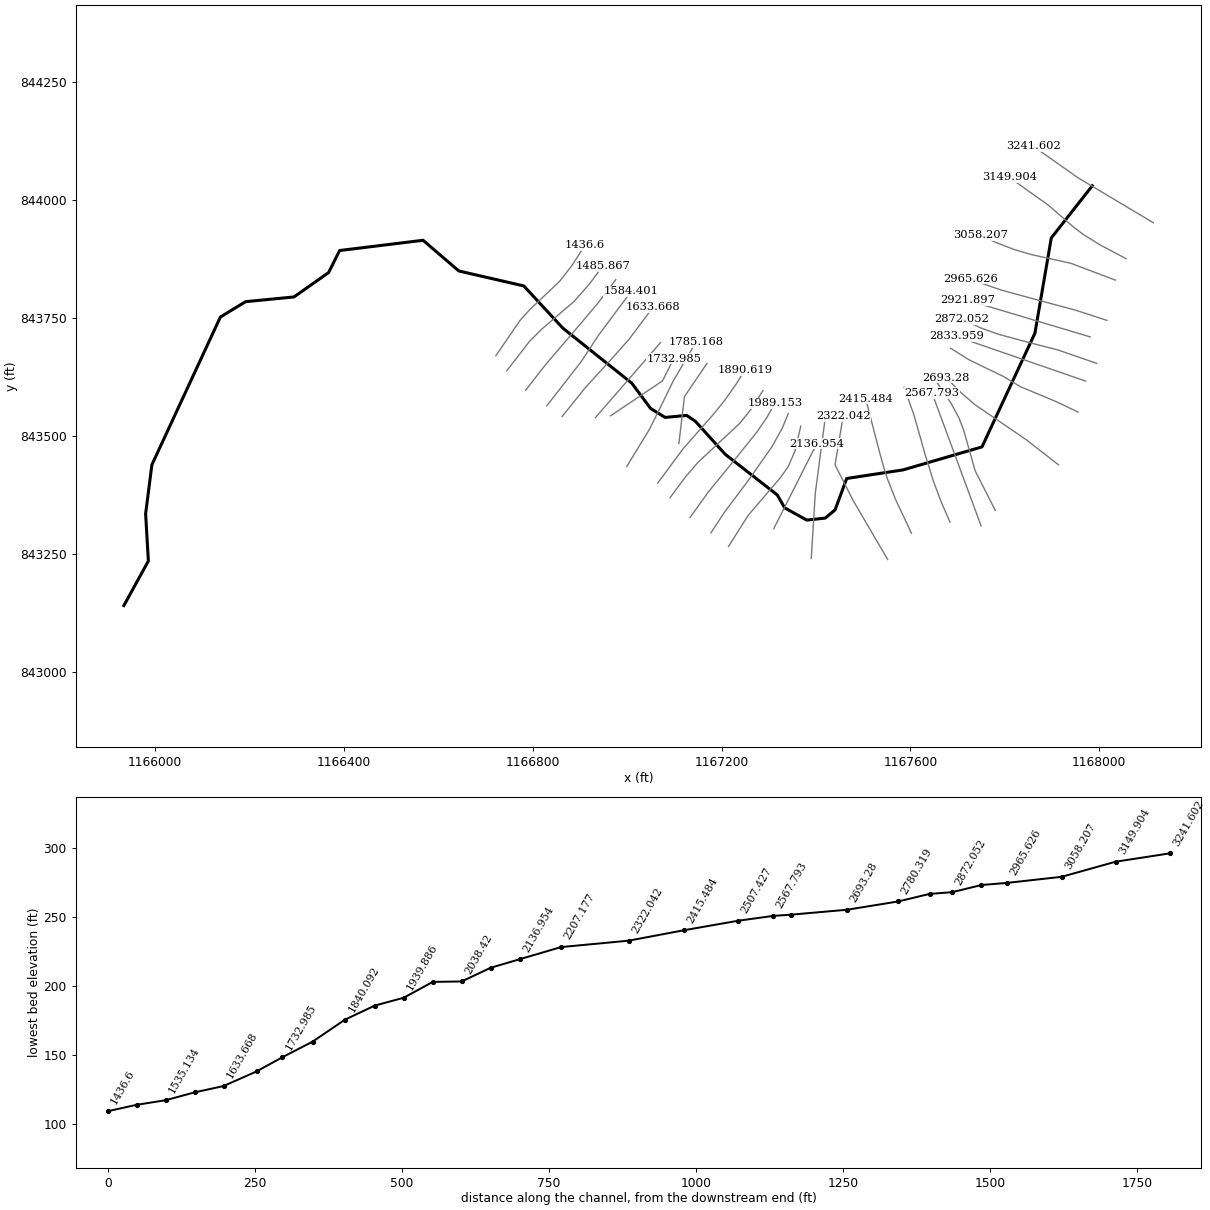
--- 32_ras.prj (project) ---

Proj Title=32
Current Plan=p01
Default Exp/Contr=0.3,0.1
English Units
Geom File=g01
Flow File=f01
Plan File=p01
Y Axis Title=Elevation
X Axis Title(PF)=Main Channel Distance
X Axis Title(XS)=Station
BEGIN DESCRIPTION:
RFD model 32 exported to HEC-RAS
END DESCRIPTION:

--- 32_ras.p01 (plan) ---

Plan Title=Plan 01
Program Version=4.10
Short Identifier=Plan 01
Geom File=g01
Flow File=f01
Subcritical Flow
Calc Critical at every XS
Secant Critical Depth

--- 32_ras.f01 (steady flow) ---

Flow Title=Flow 01
Program Version=5.01
Number of Profiles= 5
Profile Names=10yr,25yr,50yr,100yr,500yr
River Rch & RM=32,50,3241.602
   131.1  233.47  332.52  451.36  803.23
River Rch & RM=32,50,3149.904
  137.31  244.77  348.96  474.17  846.19
River Rch & RM=32,50,3058.207
  139.17  248.16  353.89  481.02  859.11
River Rch & RM=32,50,2965.626
   146.6  261.72  373.63  508.45  910.98
River Rch & RM=32,50,2872.052
  149.08  266.24  380.21  517.61  928.33
River Rch & RM=32,50,2780.319
  172.54  309.13  442.82  604.84 1094.46
River Rch & RM=32,50, 2693.28
  177.47  318.15  456.02  623.26 1129.72
River Rch & RM=32,50,2507.427
  184.24  330.56  474.17  648.62 1178.36
River Rch & RM=32,50,2322.042
  198.36  356.48  512.16  701.75 1280.62
River Rch & RM=32,50,2207.177
  203.89  366.62  527.03  722.58 1320.83
River Rch & RM=32,50,2136.954
  208.18  374.51   538.6  738.79 1352.18
River Rch & RM=32,50, 2038.42
  211.24  380.14  546.87  750.38 1374.61
River Rch & RM=32,50,1890.619
  216.14  389.15   560.1  768.94 1410.56
River Rch & RM=32,50,1785.168
  252.77  456.68  659.46  908.56 1682.61
River Rch & RM=32,50,1689.722
   261.3  472.43  682.67  941.24 1746.66
River Rch & RM=32,50,1584.401
  263.73  476.92   689.3  950.59    1765
River Rch & RM=32,50,1485.867
   268.6  485.92  702.57  969.29 1801.72
River Rch & RM=32,50,1387.333
  289.86  525.26  760.67 1051.25 1963.14
River Rch & RM=32,50,1288.799
  294.71  534.25  773.95 1070.02 2000.19
River Rch & RM=32,50,1190.265
  297.14  538.74   780.6  1079.4 2018.75
River Rch & RM=32,50,1042.464
   303.2  549.97  797.21 1102.88 2065.19
River Rch & RM=32,50,943.9305
  553.42 1017.19 1493.22  2094.1 4067.26
River Rch & RM=32,50,845.3966
  557.59 1025.02 1504.95 2110.91 4101.77
River Rch & RM=32,50,697.5958
  563.54  1036.2  1521.7 2134.92  4151.1
River Rch & RM=32,50,499.2183
  566.51 1041.79 1530.08 2146.93 4175.79
River Rch & RM=32,50,399.3746
  570.68 1049.61 1541.81 2163.75 4210.37
River Rch & RM=32,50,325.3499
  576.62 1060.79 1558.57 2187.78 4259.82
Boundary for River Rch & Prof#=32,50,1
Up Type= 0
Dn Type= 2
Boundary for River Rch & Prof#=32,50,2
Up Type= 0
Dn Type= 2
Boundary for River Rch & Prof#=32,50,2
Up Type= 0
Dn Type= 2
Boundary for River Rch & Prof#=32,50,2
Up Type= 0
Dn Type= 2
Boundary for River Rch & Prof#=32,50,2
Up Type= 0
Dn Type= 2

--- 32_ras.g01 (geometry) ---

Geom Title=32
Program Version=4.10

River Reach=32,50
Reach XY= 30
1167985.23627132844029.9169142691167898.37001261843919.457350701
1167863.71468669843717.7028134021167751.62756142843476.959161669
1167584.47154412843428.2256289121167465.11114186 843410.05645068
1167440.50647545843343.6379503461167419.67314768843326.137956083
1167380.50649235843321.971291766 1167333.8398402 843347.80461885
1167318.00651225843375.3046111761167208.00654706843461.137922332
1167144.67323431843531.1379034521167126.33990672843543.637900308
1167080.56681558 843539.338083581167049.86468998843558.344161347
1167009.90319312843611.9510473461166863.83998913 843728.63785322
1166781.34001589843817.8044959011166643.84005719843849.471157178
1166568.00674799843914.4711401461166391.34013259843892.804484963
1166368.00680479843846.1378327611166294.67349148843794.471183464
1166192.17352131843784.4711893651166138.84020269843751.971200526
1165993.74685794 843439.01187025 1165980.5069038843335.304661497
1165986.34023258843235.304690868 1165934.4280999843140.916799486

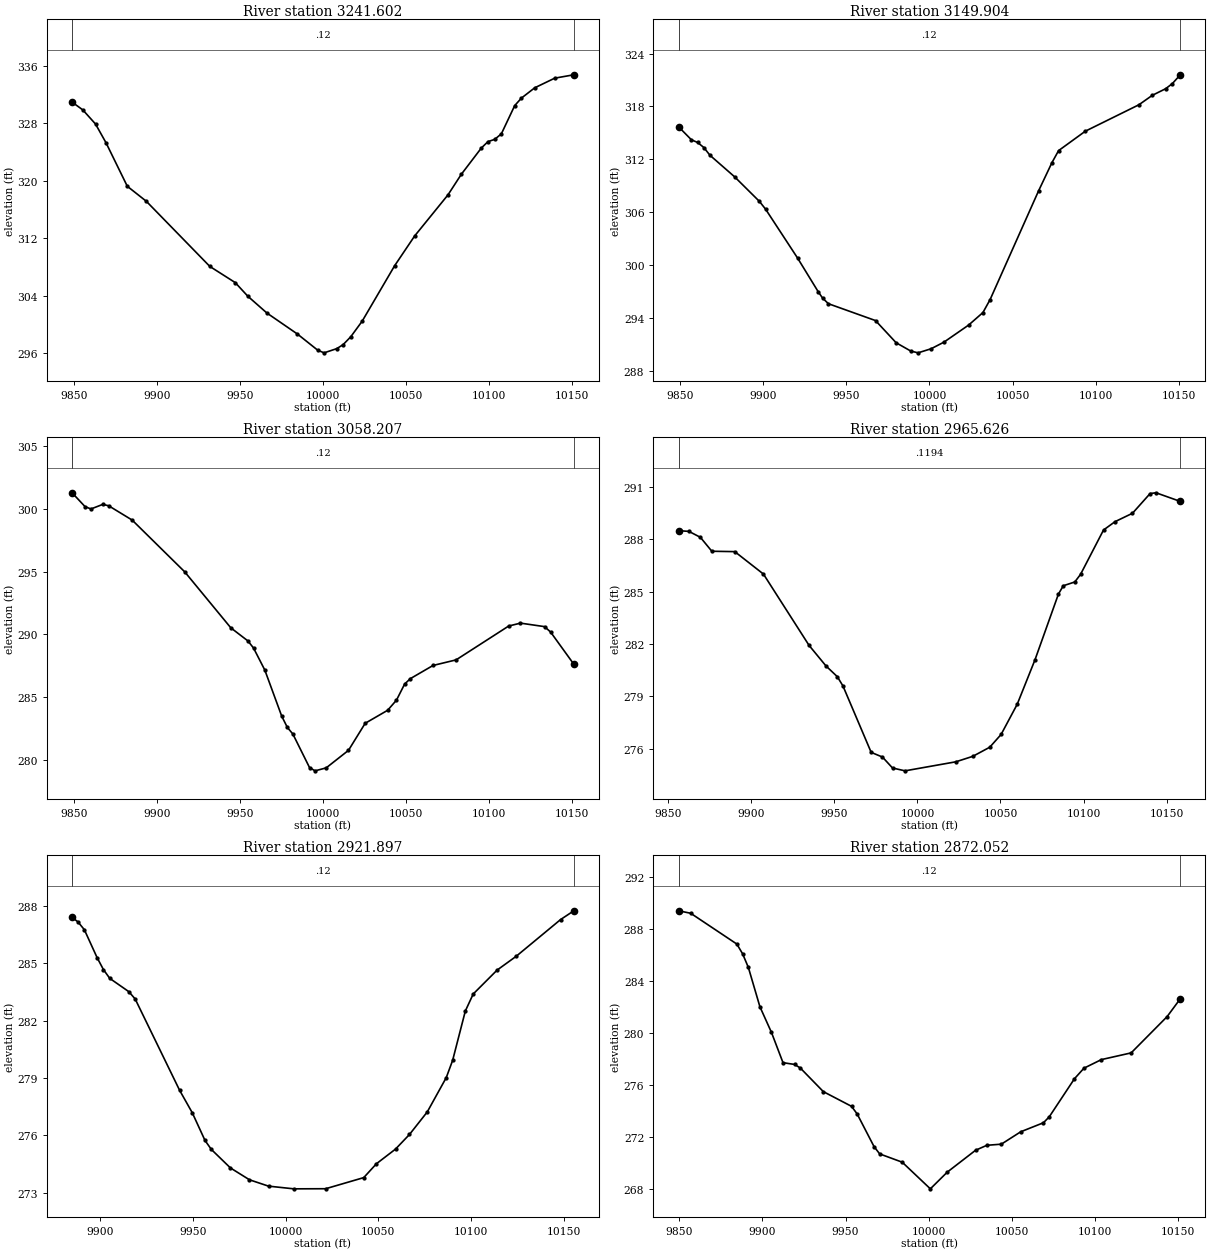
Type RM Length L Ch R = 1 ,3241.602,91.697200,91.697200,91.697200
XS GIS Cut Line= 5
1168114.39993837843951.6553423181167985.62139345 844028.55614943
1167983.87550648844029.5317921451167955.12150946844046.698041153
1167859.93792161844113.844321299
#Sta/Elev= 30
9849.008330.9186 9855.48329.82979863.123327.87029869.453325.25579882.251319.2146
9893.693317.13299931.906308.07659947.191305.82979954.834  303.929966.297 301.592
9984.637298.67619996.868296.426810000.66 296.065 10008.3296.649510012.12297.2053
10016.73298.303110023.58300.4643 10043.1308.167410055.15312.305910075.22318.0218
10083.25320.8822 10095.3324.535410099.31325.427110103.33325.735510107.34 326.504
10115.37330.427610119.39331.468710127.42332.904310139.46334.244110150.97334.7145
#Mann= 3 , 0 , 0
9849.008    0.12       09849.008    0.12       010150.97    0.12       0
#XS Ineff= 2 , 0
       0                               0
Bank Sta=9849.008,10150.97
Exp/Cntr=0.3,0.1

Type RM Length L Ch R = 1 ,3149.904,91.697100,91.697100,91.697100
XS GIS Cut Line= 6
1168056.65314962 843875.545573081168000.90107764843905.146073358
1167965.04309784843927.5414473021167944.71022799843943.202546758
1167891.89664878843989.0196058131167809.67065381844047.586796443
#Sta/Elev= 30
9849.032315.69549856.804314.21169860.519313.91149864.234313.34119867.948312.4589
9882.806310.01079897.665307.23419901.379306.35559920.646300.80479933.032296.9944
9935.747296.25179939.226295.62069967.558293.70969979.981291.19229988.758290.2546
 9993.15290.0499   10001290.512710008.68291.256310023.57293.1976 10032.2294.6212
10036.52296.095410065.63308.403810073.68311.608110077.71312.987110093.82315.1915
10126.05 318.188 10134.1319.257710142.16 320.01110146.19320.591910150.97321.5899
#Mann= 3 , 0 , 0
9849.032    0.12       09849.032    0.12       010150.97    0.12       0
#XS Ineff= 2 , 0
       0                               0
Bank Sta=9849.032,10150.97
Exp/Cntr=0.3,0.1

Type RM Length L Ch R = 1 ,3058.207,92.581600,92.581600,92.581600
XS GIS Cut Line= 6
1168034.08571664843830.147244061 1167939.6717582843865.781499317
1167857.16078859843883.9521419871167820.40310072843894.676626462
1167779.51310897843910.4314648861167748.38831564843925.005674573
#Sta/Elev= 30
 9849.02301.28959856.858300.18169860.398300.00079867.479300.36349871.019300.2562
9885.179299.11399916.776294.99329944.543290.52789954.841289.48299958.232288.9132
9965.014287.15829975.186283.48429978.544282.59419981.888282.06349991.921279.3885
9995.265279.130210001.95279.367510015.35280.7631 10025.4282.919210038.89283.9545
10044.22284.761610049.14286.046410052.56286.475710066.23287.5278 10080.1287.9726
10111.75290.670410118.84290.901610133.34290.622410136.96290.192910150.97287.6229
#Mann= 3 , 0 , 0
 9849.02    0.12       0 9849.02    0.12       010150.97    0.12       0
#XS Ineff= 2 , 0
       0                               0
Bank Sta=9849.02,10150.97
Exp/Cntr=0.3,0.1

Type RM Length L Ch R = 1 ,2965.626,43.728900,43.728900,43.728900
XS GIS Cut Line= 6
1168016.35379207 843744.81393689  1167948.492199843766.879211009
1167870.59809688843787.6822704371167794.43513252 843808.55086299
1167759.67942534843820.1734367651167727.83042094843833.085541583
#Sta/Elev= 30
9856.252288.48459862.494288.44429869.394288.10439876.293287.30649890.093287.2845
9907.343286.00069934.827281.91419945.014280.73759951.806280.12619955.202 279.594
9972.181275.79279978.972 275.5259985.022 274.8999992.556274.735710023.14275.2531
10033.35275.566710043.55276.088310050.36276.817810060.06278.546510070.77281.0955
10084.89284.860710087.79285.331710094.71285.547710098.17285.9824   10112288.5223
10118.92     28910129.43289.480910140.05290.611210143.59290.653810158.22290.1587
#Mann= 3 , 0 , 0
9856.252  0.1194       09856.252  0.1194       010158.22  0.1194       0
#XS Ineff= 2 , 0
       0                               0
Bank Sta=9856.252,10158.22
Exp/Cntr=0.3,0.1

Type RM Length L Ch R = 1 ,2921.897,49.845100,49.845100,49.845100
XS GIS Cut Line= 2
1167980.67516527843709.9054481691167721.41277114843787.391765237
#Sta/Elev= 30
  9884.9287.39699888.099287.15599891.523286.74919898.372285.29419901.796284.6662
 9905.22284.20399915.493283.50969918.917283.12799942.887278.35039949.735277.1722
9956.584275.72649960.008275.25629970.281274.29019980.553273.66929990.826273.3366
10004.52273.195310021.64273.201110042.19273.782910049.04274.508910059.31275.2734
10066.85 276.03910076.43277.2168 10086.7279.016510090.13279.918910096.98282.5004
10101.22283.3867 10114.1284.637110124.37 285.35710148.34287.280610155.49287.7395
#Mann= 3 , 0 , 0
  9884.9    0.12       0  9884.9    0.12       010155.49    0.12       0
#XS Ineff= 2 , 0
       0                               0
Bank Sta=9884.9,10155.49
Exp/Cntr=0.3,0.1

Type RM Length L Ch R = 1 ,2872.052,38.092200,38.092200,38.092200
XS GIS Cut Line= 6
1167994.35807463843653.8901263921167913.16092631843681.980062265
1167849.21909478843698.4882543121167786.23684354843715.514731937
1167748.75547319843729.0187896481167707.88473751843747.533155992
#Sta/Elev= 30
9849.544289.43219856.851 289.2419884.624286.86769888.096286.11659891.567285.0611
9898.511 282.0349905.454280.05889912.397277.7259 9919.34277.59119922.812277.3152
9936.669275.49459953.616274.36279957.005273.77689967.173271.25859970.562270.6963
9984.119 270.05710001.05268.003310011.24269.292710028.24270.974610035.03271.3587
10043.75271.444810055.43272.400410069.08273.095710072.57273.549710087.76276.4897
10093.49277.303410103.95277.962610121.87278.480710143.49 281.27510151.45282.6543
#Mann= 3 , 0 , 0
9849.544    0.12       09849.544    0.12       010151.45    0.12       0
#XS Ineff= 2 , 0
       0                               0
Bank Sta=9849.544,10151.45
Exp/Cntr=0.3,0.1

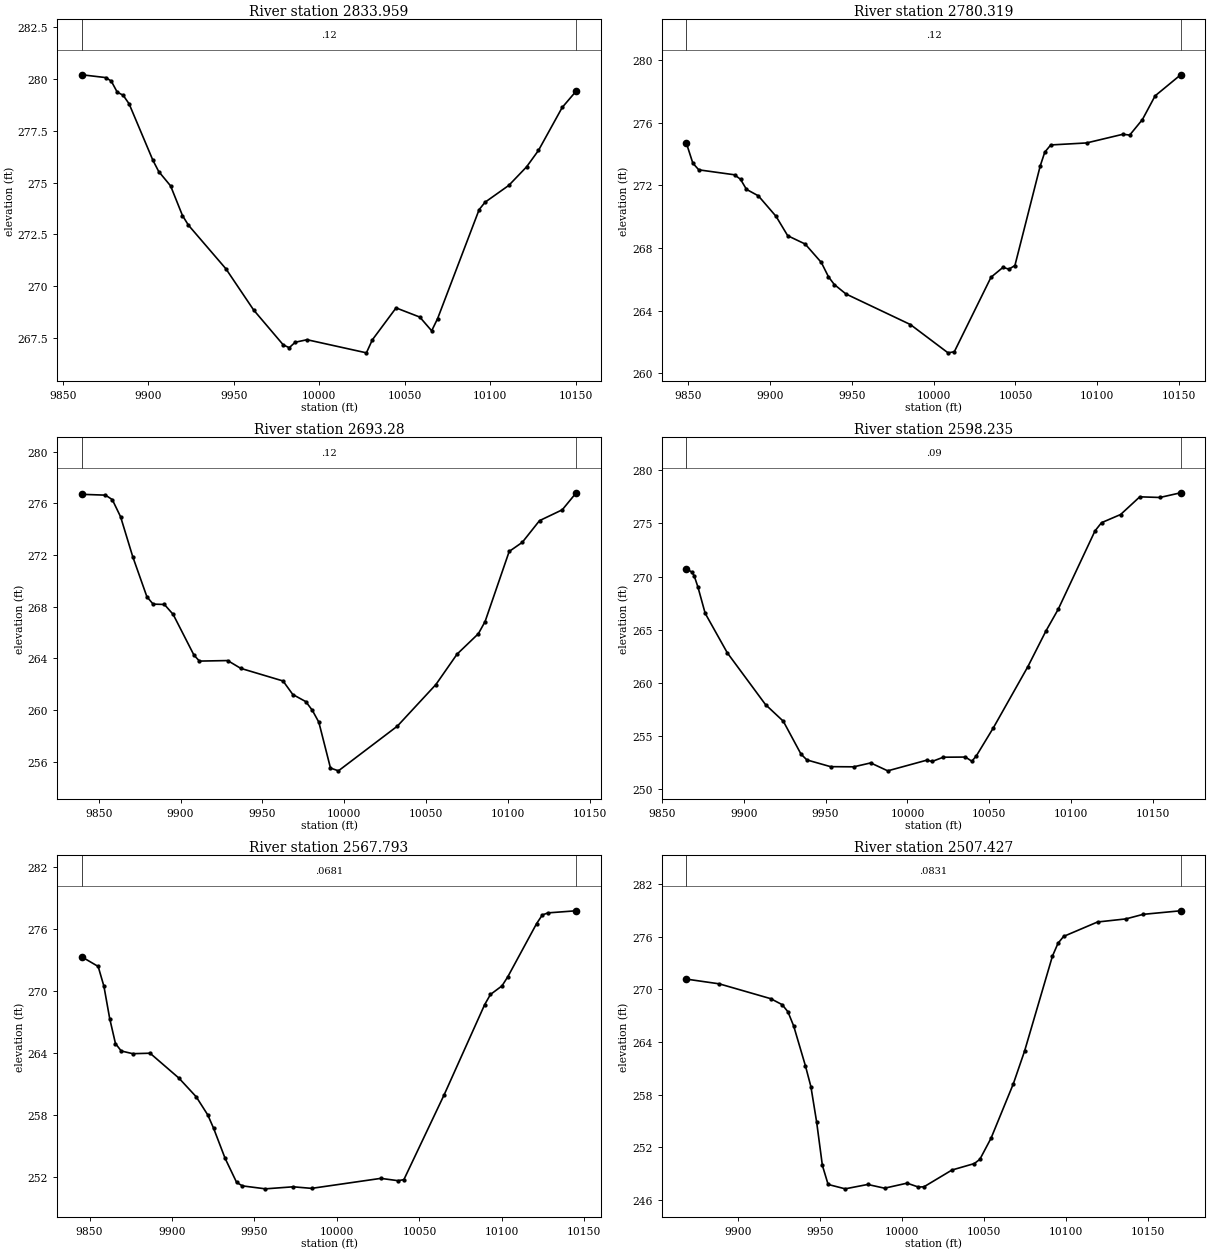
Type RM Length L Ch R = 1 ,2833.959,53.640900,53.640900,53.640900
XS GIS Cut Line= 2
1167970.92845872843616.3370652941167697.53334004843710.880118817
#Sta/Elev= 30
9861.043280.20299875.099280.06699878.273279.89679881.745279.36629885.216279.2154
9888.688278.80369902.574276.08689906.045275.53219912.988274.84049919.931273.4097
9923.403272.94699945.369270.83719961.589  268.859978.946267.16359982.417267.0335
9985.889267.29559992.832267.417210027.55266.784110031.02267.4112 10044.9268.9529
10058.79268.509810065.73267.8473 10069.2268.4349 10093.5273.695210096.98274.0533
10110.86274.864610121.28275.760810128.22276.5524 10142.1278.625410150.32279.4197
#Mann= 3 , 0 , 0
9861.043    0.12       09861.043    0.12       010150.32    0.12       0
#XS Ineff= 2 , 0
       0                               0
Bank Sta=9861.043,10150.32
Exp/Cntr=0.3,0.1

Type RM Length L Ch R = 1 ,2780.319,87.038500,87.038500,87.038500
XS GIS Cut Line= 6
1167954.98043402843550.7345620431167909.42318192  843572.5421527
 1167833.4755648843604.2093619791167797.45169438843625.858591485
1167723.49237943843661.768934979  1167685.505525843685.639364467
#Sta/Elev= 30
9849.035 274.7239853.045273.42159856.683272.99529878.507 272.6799882.144272.3923
9885.782271.74839893.056271.33289903.868270.02129910.977 268.7839921.641268.2526
9931.502267.07399935.859266.15949939.414265.66469946.523265.06139985.893 263.105
10008.86261.2969 10012.7261.365810035.12266.130610042.42266.760710046.06266.6459
10049.71266.879910065.16273.245110067.95274.126810071.59274.586610093.48274.7155
10115.65275.269510119.81275.218610127.56 276.20910135.31277.725110150.94279.0728
#Mann= 3 , 0 , 0
9849.035    0.12       09849.035    0.12       010150.94    0.12       0
#XS Ineff= 2 , 0
       0                               0
Bank Sta=9849.035,10150.94
Exp/Cntr=0.3,0.1

Type RM Length L Ch R = 1 , 2693.28,95.044700,95.044700,95.044700
XS GIS Cut Line= 6
 1167913.5668117843439.0895696451167845.78192044843491.731333637
 1167791.2259665843529.1464547671167737.28741543 843565.85137607
1167707.15492128843591.9027847421167675.49111989843623.706912605
#Sta/Elev= 30
9839.681276.69249854.135276.62899858.289 276.2839863.351274.95549870.751271.8759
9879.398268.77279883.213268.19489890.096 268.1699895.445267.40179908.137264.2535
9911.492263.78619928.761263.82669936.713263.22489962.563262.2469 9968.52261.1996
9976.472260.64869980.447259.97719984.423259.05539991.526255.50939996.383255.2922
10032.34258.748710055.91261.972410068.83 264.32410081.84265.903710085.94266.8457
10100.66272.270410108.66272.976710119.18274.654910133.07275.494410141.61276.8124
#Mann= 3 , 0 , 0
9839.681    0.12       09839.681    0.12       010141.61    0.12       0
#XS Ineff= 2 , 0
       0                               0
Bank Sta=9839.681,10141.61
Exp/Cntr=0.3,0.1

Type RM Length L Ch R = 1 ,2598.235,30.442300,30.442300,30.442300
XS GIS Cut Line= 6
1167779.80311773843342.4218492021167736.99341175843426.730672394
1167713.20040576843511.1430222451167702.95964922843538.130049847
1167685.72442135843569.9673299361167655.20376296843615.034001443
#Sta/Elev= 30
9864.923270.73799868.263270.42049869.708270.08759872.016269.02319876.462266.5451
 9889.97262.83519913.304257.9729 9924.17256.41059934.992253.3189  9938.6252.7745
9953.029252.14439967.144252.12869977.536252.49549987.927251.7518 10011.7252.7507
10015.08252.633910021.83253.031410035.36253.045910039.32252.651510042.12253.1792
10052.46255.800110073.51 261.54110084.53264.8854   10092266.9171 10114.5274.2869
10118.47275.055810130.14275.825510141.84277.485810154.13277.424610166.82277.8658
#Mann= 3 , 0 , 0
9864.923    0.09       09864.923    0.09       010166.82    0.09       0
#XS Ineff= 2 , 0
       0                               0
Bank Sta=9864.923,10166.82
Exp/Cntr=0.3,0.1

Type RM Length L Ch R = 1 ,2567.793,60.366100,60.366100,60.366100
XS GIS Cut Line= 2
1167749.67822009843309.8031443511167645.87579539843590.995628268
#Sta/Elev= 30
9845.319 273.3099855.223272.3835 9858.72270.46169862.218 267.3349865.715264.9144
9869.212264.19619876.207263.93389886.698  263.989904.184261.56919914.676259.7577
9921.671258.00459925.168256.72699932.162253.80739939.157 251.4719942.654251.1314
9956.643250.84549973.464251.04259984.621250.891410026.59251.859210037.08251.6337
10040.58251.740710065.06259.980710089.54268.682210093.04269.666910100.03270.4992
10103.53271.371810121.01276.526610124.51 277.37210128.01277.571510145.06 277.774
#Mann= 3 , 0 , 0
9845.319  0.0681       09845.319  0.0681       010145.06  0.0681       0
#XS Ineff= 2 , 0
       0                               0
Bank Sta=9845.319,10145.06
Exp/Cntr=0.3,0.1

Type RM Length L Ch R = 1 ,2507.427,91.943000,91.943000,91.943000
XS GIS Cut Line= 6
1167683.84730378843317.6363867521167666.25309182843357.833976465
1167649.27299564843402.9103706581167631.41424623843460.124769013
1167607.79496832843543.7205987291167586.75839839843603.221394416
#Sta/Elev= 30
9868.171271.17759888.308270.63669919.736268.94759926.748268.26449930.254 267.456
 9933.76265.83839940.887261.33429944.277258.93359947.783254.90479951.289249.9625
9954.795247.79119965.213247.29099978.963247.78879989.276247.364710003.03 247.939
 10009.9247.495810013.34247.523710030.43249.433510044.07 250.16710047.48250.6552
 10054.3 253.05710067.93259.260910074.75262.9591 10091.8273.793210095.21275.2596
10098.62276.036710119.32277.679410136.72278.032810147.16278.550210170.13278.9572
#Mann= 3 , 0 , 0
9868.171  0.0831       09868.171  0.0831       010170.13  0.0831       0
#XS Ineff= 2 , 0
       0                               0
Bank Sta=9868.171,10170.13
Exp/Cntr=0.3,0.1

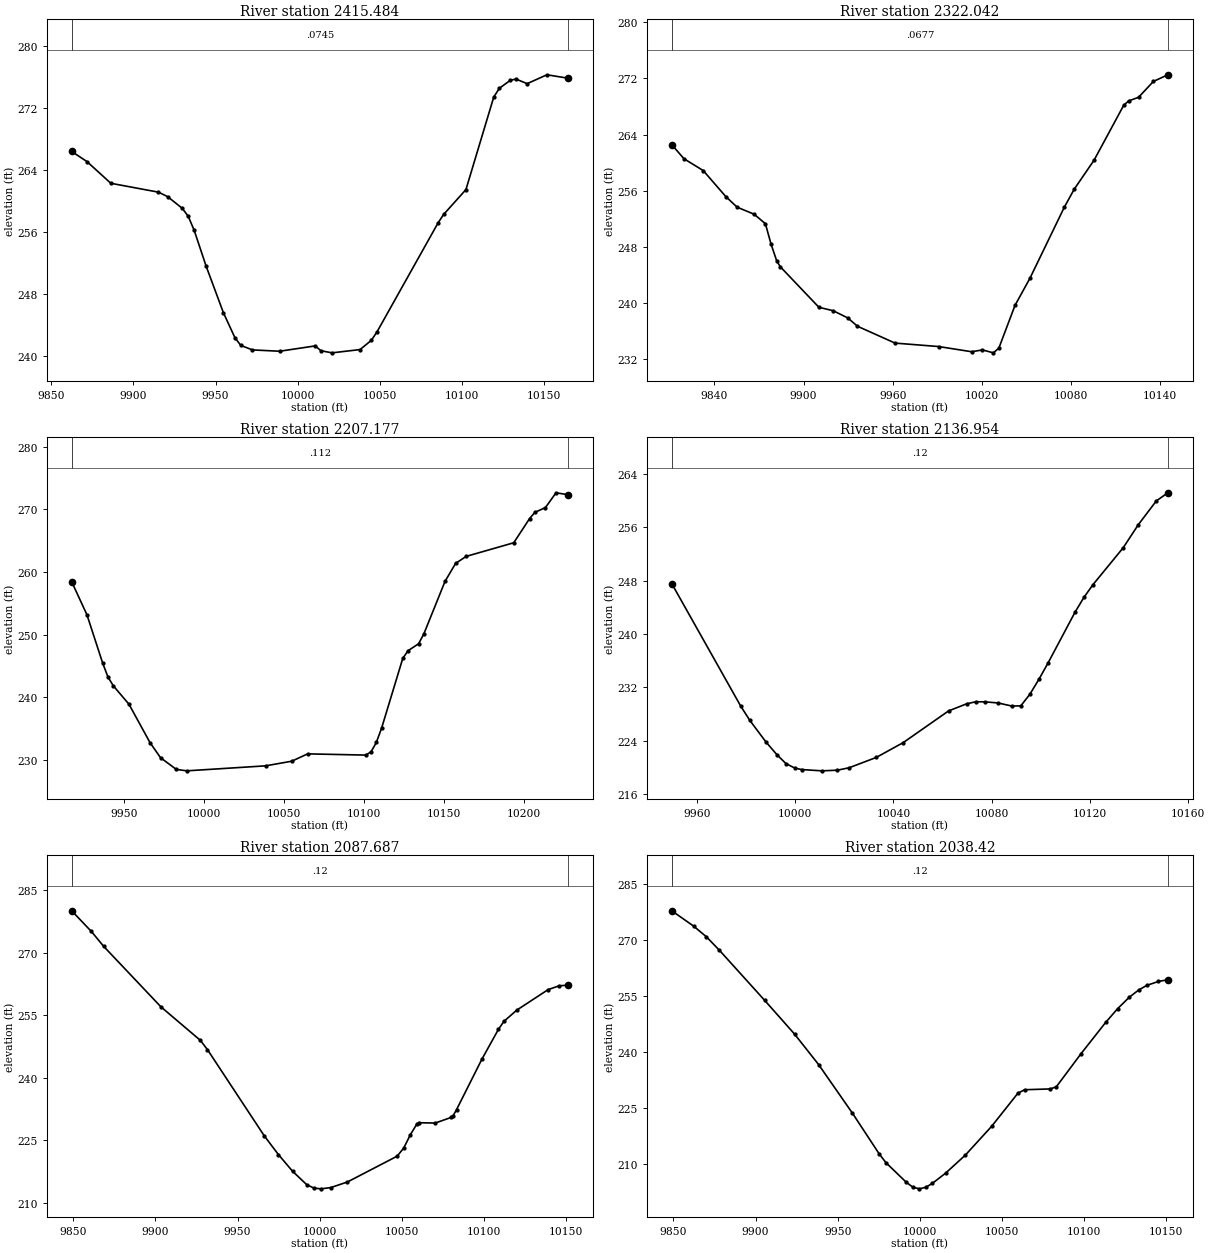
Type RM Length L Ch R = 1 ,2415.484,93.442400,93.442400,93.442400
XS GIS Cut Line= 6
1167602.20675698843294.2356449941167568.28446816843366.379232543
1167550.91872443843410.466347547 1167543.4593694843434.195874689
1167534.46514387843466.457943713 1167505.2688816843579.243433272
#Sta/Elev= 30
 9862.41 266.3989871.753265.08539886.254262.28859915.258261.14389920.831260.5642
 9929.76259.05479933.385258.0189 9937.01256.21019944.203251.63219954.781245.5895
9961.834242.3459 9965.36 241.3779972.412 240.7979989.017240.623610010.68241.3127
10014.11240.689510020.92240.417610037.95240.839810044.76242.020210048.17243.0841
10085.44257.178510088.83 258.27410102.39261.469910119.33273.407410122.72274.5369
 10129.5275.586510132.89  275.7310139.67  275.1410151.69276.285410164.39  275.85
#Mann= 3 , 0 , 0
 9862.41  0.0745       0 9862.41  0.0745       010164.39  0.0745       0
#XS Ineff= 2 , 0
       0                               0
Bank Sta=9862.41,10164.39
Exp/Cntr=0.3,0.1

Type RM Length L Ch R = 1 ,2322.042,114.865100,114.865100,114.865100
XS GIS Cut Line= 4
1167551.97740057843238.4687790721167479.05264017843362.869840965
1167440.44541407 843439.01187025 1167457.6041812843541.964473188
#Sta/Elev= 30
9811.307262.55839819.527 260.5579832.508258.8683 9847.72255.16169855.326253.6557
9866.735252.66039874.341251.30149878.144   248.49881.947246.01349884.402245.1704
9910.352239.40549919.977238.91639929.814237.88719936.301236.70739961.603234.3073
9991.031233.8142 10013.1233.078610020.46233.333910027.82232.919910031.49233.5977
10042.37239.688810052.35243.519510075.63253.693210082.28256.248210095.59260.3591
10115.55268.180210118.87268.791410125.52269.3067 10135.5 271.56510145.25 272.512
#Mann= 3 , 0 , 0
9811.307  0.0677       09811.307  0.0677       010145.25  0.0677       0
#XS Ineff= 2 , 0
       0                               0
Bank Sta=9811.307,10145.25
Exp/Cntr=0.3,0.1

Type RM Length L Ch R = 1 ,2207.177,70.223000,70.223000,70.223000
XS GIS Cut Line= 3
1167390.04153553 843240.613624961167398.62091911843378.956185192
1167421.14180097843549.471433818
#Sta/Elev= 30
9916.922258.46599926.523253.16179936.384245.43779939.672243.24679942.959241.8656
 9952.82238.90679965.969232.79229972.543230.38939982.404228.52019988.979228.2865
10038.29229.082910054.72229.822410064.64230.994810101.05230.798110104.36231.3181
10107.67232.812910110.97235.100110124.21246.215110127.52247.450310134.14248.5603
10137.45 250.15310150.69258.5189 10157.3261.380210163.92262.496210193.71264.6703
10203.64268.540210206.94269.521210213.56270.288910220.18272.644210227.53272.3461
#Mann= 3 , 0 , 0
9916.922   0.112       09916.922   0.112       010227.53   0.112       0
#XS Ineff= 2 , 0
       0                               0
Bank Sta=9916.922,10227.53
Exp/Cntr=0.3,0.1

Type RM Length L Ch R = 1 ,2136.954,49.266900,49.266900,49.266900
XS GIS Cut Line= 2
1167310.68223742843303.8865788731167401.83818793843484.053634048
#Sta/Elev= 30
 9949.81247.57279977.884 229.195 9981.56227.0685 9988.18223.80669992.591221.9225
9996.268220.58189999.945219.897310002.71219.683910010.98219.492610017.25 219.591
10022.01219.957310033.04221.503610044.07223.741110062.45228.476710069.81229.5442
10073.48229.850610077.16229.845810082.65229.672110088.19229.212210091.87229.2446
10095.54230.970210099.22233.2117 10102.9235.633410113.93  243.29 10117.6245.5373
10121.28247.441810133.52252.944310139.67256.407310147.02259.982710151.72261.2003
#Mann= 3 , 0 , 0
 9949.81    0.12       0 9949.81    0.12       010151.72    0.12       0
#XS Ineff= 2 , 0
       0                               0
Bank Sta=9949.81,10151.72
Exp/Cntr=0.3,0.1

Type RM Length L Ch R = 1 ,2087.687,49.267000,49.267000,49.267000
XS GIS Cut Line= 6
1167214.83569261843266.1311189441167256.54188465843331.997748698
1167324.38110653843411.3283914311167341.08005622843434.863929159
1167355.52235648843468.0023187551167367.85022079843520.996754832
#Sta/Elev= 30
9849.045 280.123 9860.98275.18119868.574271.55659903.373257.04069927.355248.9977
9931.673246.7702 9966.22226.06899974.857221.55699983.494 217.5359992.131214.3098
9996.449213.512410000.77213.3258 10006.7 213.62810016.81214.969210047.08221.1682
10051.11 223.12710055.13226.324410059.15228.934210060.31229.210710070.26229.1301
10079.93230.475210081.19230.911510083.21232.330610098.58244.405910108.68251.6099
10112.05253.553610119.86256.2498   10139261.194810145.73262.105210150.92262.2466
#Mann= 3 , 0 , 0
9849.045    0.12       09849.045    0.12       010150.92    0.12       0
#XS Ineff= 2 , 0
       0                               0
Bank Sta=9849.045,10150.92
Exp/Cntr=0.3,0.1

Type RM Length L Ch R = 1 , 2038.42,49.266900,49.266900,49.266900
XS GIS Cut Line= 6
1167177.59570591843294.9149756051167206.78304665843339.275466542
1167258.48776754 843408.25899745 1167306.9141558 843477.45590889
1167328.20376738843515.7369381971167341.40135831 843547.46288269
#Sta/Elev= 30
9849.017277.93449862.252273.84969870.106270.95919877.961267.38169905.599253.9166
9923.718244.91629938.399 236.729  9958.9 223.762  9975.3212.7796  9979.4 210.443
9991.635205.24519995.654203.90869999.668 203.44310003.66203.862210007.67204.9291
10015.67207.643110027.68212.474910043.69220.1912 10059.7229.072410063.79229.9942
10079.29230.206110083.04 230.76810098.06239.630210113.07248.018210120.37251.7141
10127.47254.779210133.16256.704810138.14257.954510145.24259.004210150.95259.4562
#Mann= 3 , 0 , 0
9849.017    0.12       09849.017    0.12       010150.95    0.12       0
#XS Ineff= 2 , 0
       0                               0
Bank Sta=9849.017,10150.95
Exp/Cntr=0.3,0.1

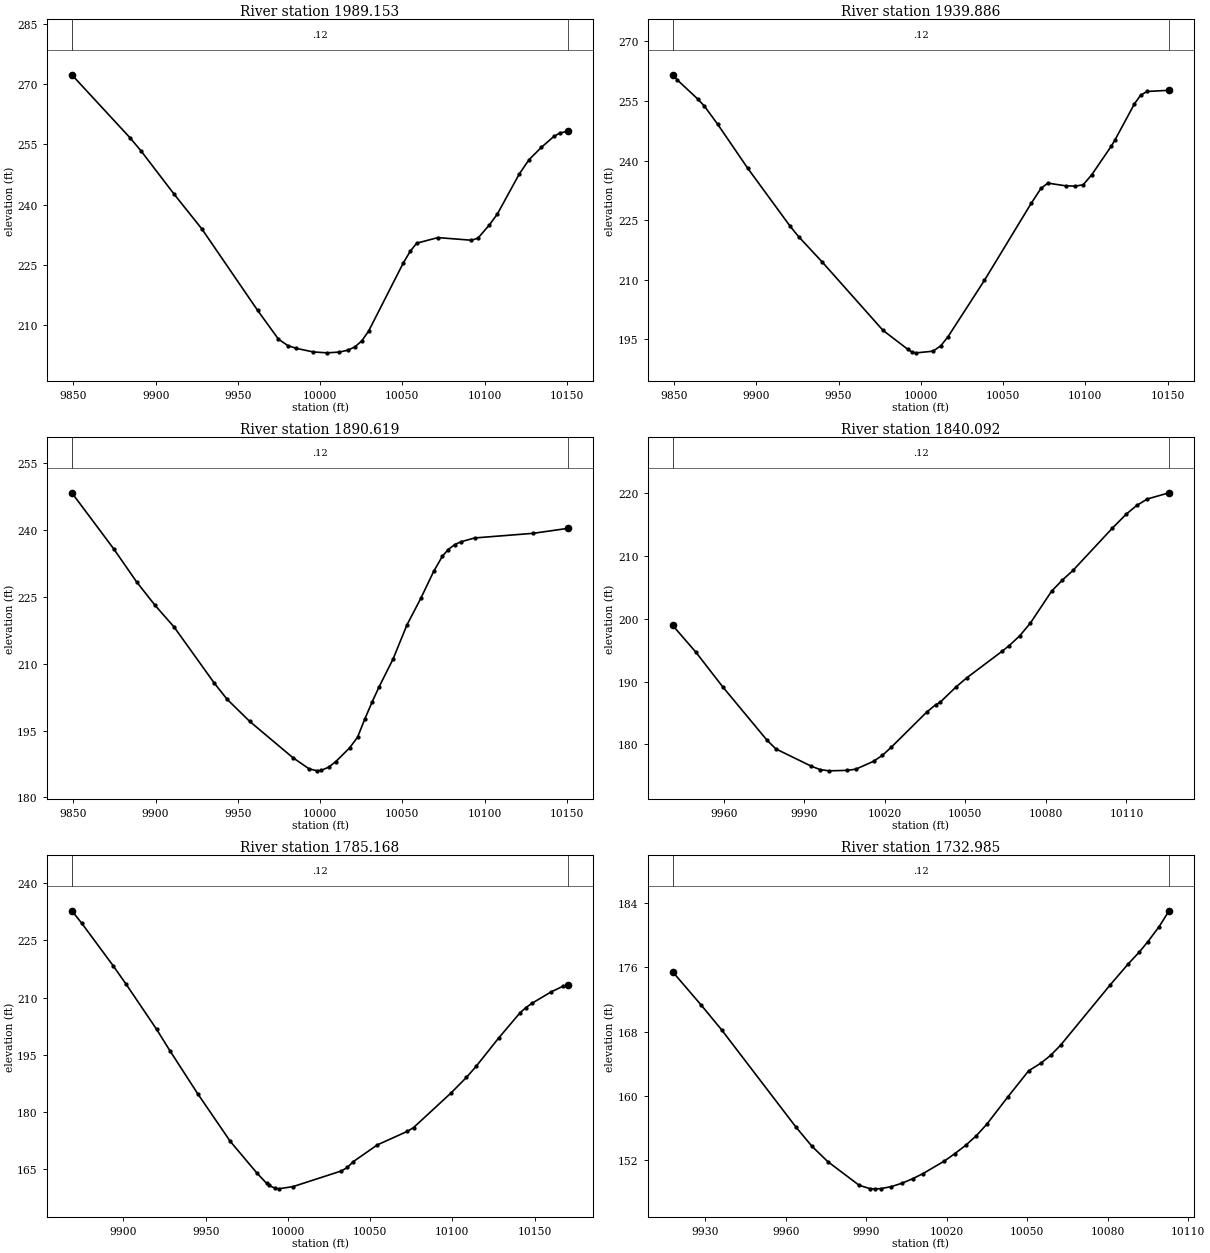
Type RM Length L Ch R = 1 ,1989.153,49.266900,49.266900,49.266900
XS GIS Cut Line= 6
1167133.44445343843327.4784178911167171.66702031843380.822589254
1167224.95429686843446.2133719291167275.69361257843509.310263512
1167296.31482668843539.5983296371167312.99116531843569.641682143
#Sta/Elev= 30
9849.022272.35019884.521256.61339891.177253.35599911.358 242.5459928.127233.9463
9961.985213.67949974.682206.49679980.354204.90749985.548204.20619995.843203.3149
10004.28203.093110011.62203.282610016.91203.750110021.12 204.56910025.33206.0615
10029.54208.540310050.59225.4726 10054.8228.385910058.73230.401610071.64231.7973
10091.96 231.14110095.93231.640210102.96 234.96410107.84237.705610121.06   247.6
10127.08251.217110134.58254.278110142.09256.977210145.84257.854710150.97258.3145
#Mann= 3 , 0 , 0
9849.022    0.12       09849.022    0.12       010150.97    0.12       0
#XS Ineff= 2 , 0
       0                               0
Bank Sta=9849.022,10150.97
Exp/Cntr=0.3,0.1

Type RM Length L Ch R = 1 ,1939.886,49.267000,49.267000,49.267000
XS GIS Cut Line= 6
1167090.88331136 843369.16605481 1167123.7658045843413.588175021
1167150.41407441843444.4507250841167238.91202798843527.058261442
1167263.70064369843558.2356548161167287.73124971843596.117996498
#Sta/Elev= 30
9849.034261.56889852.047260.23319864.292255.50599868.374253.71339876.538249.0991
9894.664 238.1139920.628223.43519925.648220.89029939.838214.58089976.986197.2961
9992.231192.48469994.895191.74359997.313191.641110007.43192.055610012.15193.4309
10016.47195.6569 10038.7209.892710067.07229.215410073.01232.9721 10077.2234.3274
10088.15233.637610093.96233.5667 10098.7233.902810103.97236.452810115.88243.6811
10118.16245.272210129.82254.2214 10133.7256.471310137.59257.369110150.94257.6678
#Mann= 3 , 0 , 0
9849.034    0.12       09849.034    0.12       010150.94    0.12       0
#XS Ineff= 2 , 0
       0                               0
Bank Sta=9849.034,10150.94
Exp/Cntr=0.3,0.1

Type RM Length L Ch R = 1 ,1890.619,50.526700,50.526700,50.526700
XS GIS Cut Line= 6
1167064.95425794843400.3480151511167118.89999166 843473.22983263
1167181.53020763843544.3706980981167205.68803732843574.086257817
 1167231.0093002843609.8529341071167248.97116638843639.153773152
#Sta/Elev= 30
9849.035248.3509 9874.48235.78799888.618228.26599899.647223.10139911.216218.2408
9935.707205.62829943.376202.0597 9957.22197.0517 9983.36 188.947 9993.24186.4268
9998.227185.962410000.81186.073810005.21186.7842 10009.6188.055810017.95191.1132
10022.78193.498210027.18 197.57510031.57201.350910035.91204.831410044.37211.0361
10052.82218.700810061.28224.686110069.06230.697110074.39234.117810077.93235.6186
10081.95236.745110085.75 237.36610094.01 238.21510129.61239.255510150.98240.3826
#Mann= 3 , 0 , 0
9849.035    0.12       09849.035    0.12       010150.98    0.12       0
#XS Ineff= 2 , 0
       0                               0
Bank Sta=9849.035,10150.98
Exp/Cntr=0.3,0.1

Type RM Length L Ch R = 1 ,1840.092,54.924300,54.924300,54.924300
XS GIS Cut Line= 3
1167109.80693522843484.2691915781167121.50298306843583.198263049
1167169.26184514843653.861885503
#Sta/Elev= 30
9940.958198.95579949.728194.62499959.639  189.169976.157180.65449979.461  179.28
9992.676 176.5249995.979175.98529999.283175.794210005.89175.865210009.19176.0547
 10015.8177.307910019.11178.255210022.41179.544510035.62185.136810038.93   186.3
10040.58186.687610046.52189.130210050.48  190.5710063.67194.805710066.32195.7067
10070.28197.277210074.24199.309710082.16204.386610086.12206.127510090.08207.6663
10104.68214.358310109.88216.602410113.84218.0106 10117.8219.029710125.87220.0155
#Mann= 3 , 0 , 0
9940.958    0.12       09940.958    0.12       010125.87    0.12       0
#XS Ineff= 2 , 0
       0                               0
Bank Sta=9940.958,10125.87
Exp/Cntr=0.3,0.1

Type RM Length L Ch R = 1 ,1785.168,52.182900,52.182900,52.182900
XS GIS Cut Line= 6
1166999.28266702843435.332204111 1167046.5871468843512.661966958
1167073.07389852843565.7409604941167073.92791118843567.549457764
1167097.57624676843616.0216143591167146.02039694843698.957842844
#Sta/Elev= 30
9868.612 232.6979874.652229.43799893.882218.24259901.574213.51829920.133 201.709
9928.496195.91639945.281184.75319964.966172.35719981.264164.0253 9987.01161.3864
9988.597160.81579992.264160.06889994.358159.933210003.26160.532610032.52164.6134
10036.17165.542510039.82  167.0710054.43171.440410072.68174.9838 10076.4175.9571
 10099.2185.014510108.57189.0938 10114.4191.948110128.08199.348510141.09205.9609
10144.79207.385710148.59208.531610159.99211.445310167.11212.913910170.56213.2698
#Mann= 3 , 0 , 0
9868.612    0.12       09868.612    0.12       010170.56    0.12       0
#XS Ineff= 2 , 0
       0                               0
Bank Sta=9868.612,10170.56
Exp/Cntr=0.3,0.1

Type RM Length L Ch R = 1 ,1732.985,43.263100,43.263100,43.263100
XS GIS Cut Line= 3
1166965.06834295843542.7494308651167075.20612696843616.824400634
1167098.59822267843663.608592063
#Sta/Elev= 30
9917.833175.4474 9928.59171.26289936.113168.2246 9963.79156.14869969.741153.7636
9975.651151.85199987.377148.90029991.467148.47799993.256148.4585 9995.42148.4792
9999.374148.737910003.33149.158110007.28149.709910011.24150.364110019.14151.9155
 10023.1152.849810027.05153.862210031.01155.048910034.96156.492810042.87159.9199
10050.56163.136310055.16164.089910058.82165.070310062.49166.327910080.83173.7633
10087.63176.402710091.84177.911110094.97 179.17810099.17181.047110102.87183.0121
#Mann= 3 , 0 , 0
9917.833    0.12       09917.833    0.12       010102.87    0.12       0
#XS Ineff= 2 , 0
       0                               0
Bank Sta=9917.833,10102.87
Exp/Cntr=0.3,0.1

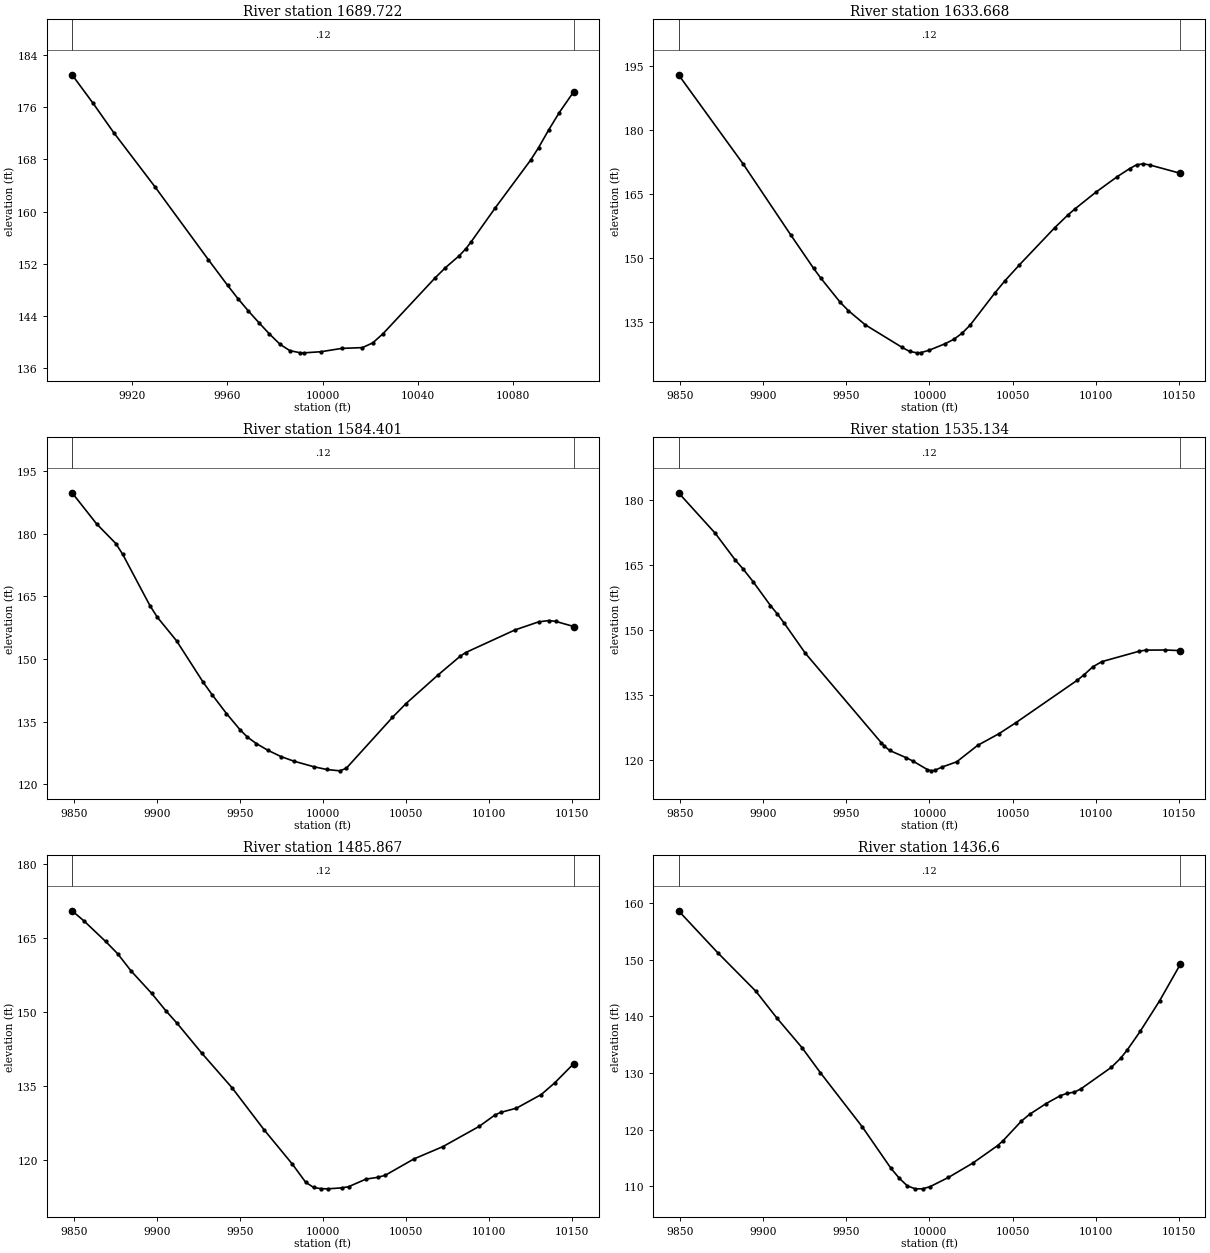
Type RM Length L Ch R = 1 ,1689.722,56.054100,56.054100,56.054100
XS GIS Cut Line= 2
1166932.90421134843538.8507482261167070.82010904843697.722064972
#Sta/Elev= 30
9894.992180.9869 9903.76176.63519912.449172.11979929.828163.76299952.181152.5985
 9960.24148.66119964.584146.62939968.929 144.7439973.273142.98099977.618 141.273
9982.209139.62929986.307138.66569990.652138.33829992.218138.32849999.341138.4973
10008.03139.009210016.72  139.1310021.06139.855510025.41141.279810047.13149.7985
10051.48151.375710057.28153.211910060.17154.325910062.28155.341410072.29160.5018
10087.31167.928510090.58169.810310094.92 172.58210099.27175.194210105.38178.4204
#Mann= 3 , 0 , 0
9894.992    0.12       09894.992    0.12       010105.38    0.12       0
#XS Ineff= 2 , 0
       0                               0
Bank Sta=9894.992,10105.38
Exp/Cntr=0.3,0.1

Type RM Length L Ch R = 1 ,1633.668,49.266900,49.266900,49.266900
XS GIS Cut Line= 6
1166862.50651673843541.3577603941166911.74679167843602.507633942
1166959.92633585843655.2927148461166961.39385724843656.651530868
1167004.46348005843705.2127267711167055.50114734843773.247177596
#Sta/Elev= 30
9849.022192.89599888.002171.9508 9916.42155.45519930.267 147.5749934.709145.2259
9946.394139.55689951.261 137.6359961.361134.33349983.571129.03419988.013128.1055
9992.455 127.763 9995.06127.82739999.852128.379410009.62129.926810014.65130.9316
10019.51132.314910024.45134.241310039.29141.753810045.35144.608210054.12148.3635
10075.39157.078310083.59160.156510087.69161.518110099.99165.349210113.01169.0333
 10120.5170.9248 10124.6171.7966 10128.7172.044410132.81171.744110150.96169.8163
#Mann= 3 , 0 , 0
9849.022    0.12       09849.022    0.12       010150.96    0.12       0
#XS Ineff= 2 , 0
       0                               0
Bank Sta=9849.022,10150.96
Exp/Cntr=0.3,0.1

Type RM Length L Ch R = 1 ,1584.401,49.266900,49.266900,49.266900
XS GIS Cut Line= 6
1166830.06560145843564.0449367771166901.66325407843655.944712252
1166920.22212473843683.8090486761166921.25111629843685.524034499
1166939.64937448843713.4983008731167009.29870448 843806.88187134
#Sta/Elev= 30
9849.023189.86169863.821182.39419875.386177.67939879.545175.06329895.851162.8212
 9900.34 160.0169911.866154.38639927.881144.45299933.219141.4871 9941.93136.9279
9950.248132.97359954.573131.26339959.911129.72319966.813128.12759974.697126.6132
9982.581125.49179994.406124.175210002.22123.509610010.08123.183110014.01123.7849
10041.79135.992810049.98139.317310069.44146.239910082.72150.708310085.91151.5567
10115.46156.957210129.81158.911310135.93159.219210140.02159.026810150.98157.7827
#Mann= 3 , 0 , 0
9849.023    0.12       09849.023    0.12       010150.98    0.12       0
#XS Ineff= 2 , 0
       0                               0
Bank Sta=9849.023,10150.98
Exp/Cntr=0.3,0.1

Type RM Length L Ch R = 1 ,1535.134,49.267000,49.267000,49.267000
XS GIS Cut Line= 6
1166785.28908872843596.9755366911166828.93485147843652.987340654
 1166880.3647515843712.9192009351166881.67831303843714.427364089
1166937.32735977 843780.088423791166976.04090962843830.943483286
#Sta/Elev= 30
9849.017181.59829871.068172.27999883.286166.03319887.705164.11359893.961161.0699
9904.342155.59849908.501153.65329912.661151.5136 9925.34144.59679970.994 123.991
9972.896123.22129976.032122.19799986.108120.50759990.189119.72479998.835117.7752
10001.21117.497710003.16117.597510007.46118.349510016.43119.581510028.96123.3553
10041.87126.063610051.95128.580110089.09138.418610093.21   139.710098.33141.4799
10103.75142.6722 10126.2145.069310130.32145.330710141.66145.353310150.98145.2183
#Mann= 3 , 0 , 0
9849.017    0.12       09849.017    0.12       010150.98    0.12       0
#XS Ineff= 2 , 0
       0                               0
Bank Sta=9849.017,10150.98
Exp/Cntr=0.3,0.1

Type RM Length L Ch R = 1 ,1485.867,49.266900,49.266900,49.266900
XS GIS Cut Line= 6
 1166745.2897733843638.1251412651166793.05342974843699.966777689
1166820.12634369843727.0382360451166887.85756409843785.050408637
1166919.97486215843821.4825234371166948.29146911843859.785419812
#Sta/Elev= 30
9849.044 170.5529856.171168.50669869.239 164.3319876.429 161.8649884.533158.3642
9896.847153.83859905.418150.30439912.207147.74929927.232141.62949945.374134.6408
9964.598126.13949981.664119.15429989.586115.51059994.405114.45299998.652114.2161
 10002.8114.177510011.21114.371810015.42114.611710025.87116.150110032.97116.5136
10037.47116.926810054.75120.244310072.14122.735610094.01126.847110103.32129.1155
10106.88129.672910116.39130.528910131.36133.303610139.52135.690610150.95139.5854
#Mann= 3 , 0 , 0
9849.044    0.12       09849.044    0.12       010150.95    0.12       0
#XS Ineff= 2 , 0
       0                               0
Bank Sta=9849.044,10150.95
Exp/Cntr=0.3,0.1

Type RM Length L Ch R = 1 ,  1436.6,49.267000,49.267000,49.267000
XS GIS Cut Line= 6
 1166722.1307262843669.996087842 1166773.3920648843744.700465013
1166794.56806265843768.2071283621166857.58172897843828.006643213
1166883.58444946843861.5612700481166910.90689703843903.701555248
#Sta/Elev= 30
9849.043158.67459872.585151.27379895.584144.44869908.253139.7037 9923.31134.4911
9934.401130.05229959.524120.51549976.806113.1758 9981.74111.44389986.674  110.06
9991.498109.5309 9995.89109.540710000.29109.904810011.38111.537710026.02 114.068
10040.98 117.16510044.24118.017610055.34121.505210060.34122.719410070.25  124.61
10078.55125.9652 10082.7126.405510087.12126.6121   10091127.173710109.53131.0244
10115.03132.616710118.94134.043910126.76137.344810138.49142.765610150.95 149.215
#Mann= 3 , 0 , 0
9849.043    0.12       09849.043    0.12       010150.95    0.12       0
#XS Ineff= 2 , 0
       0                               0
Bank Sta=9849.043,10150.95
Exp/Cntr=0.3,0.1