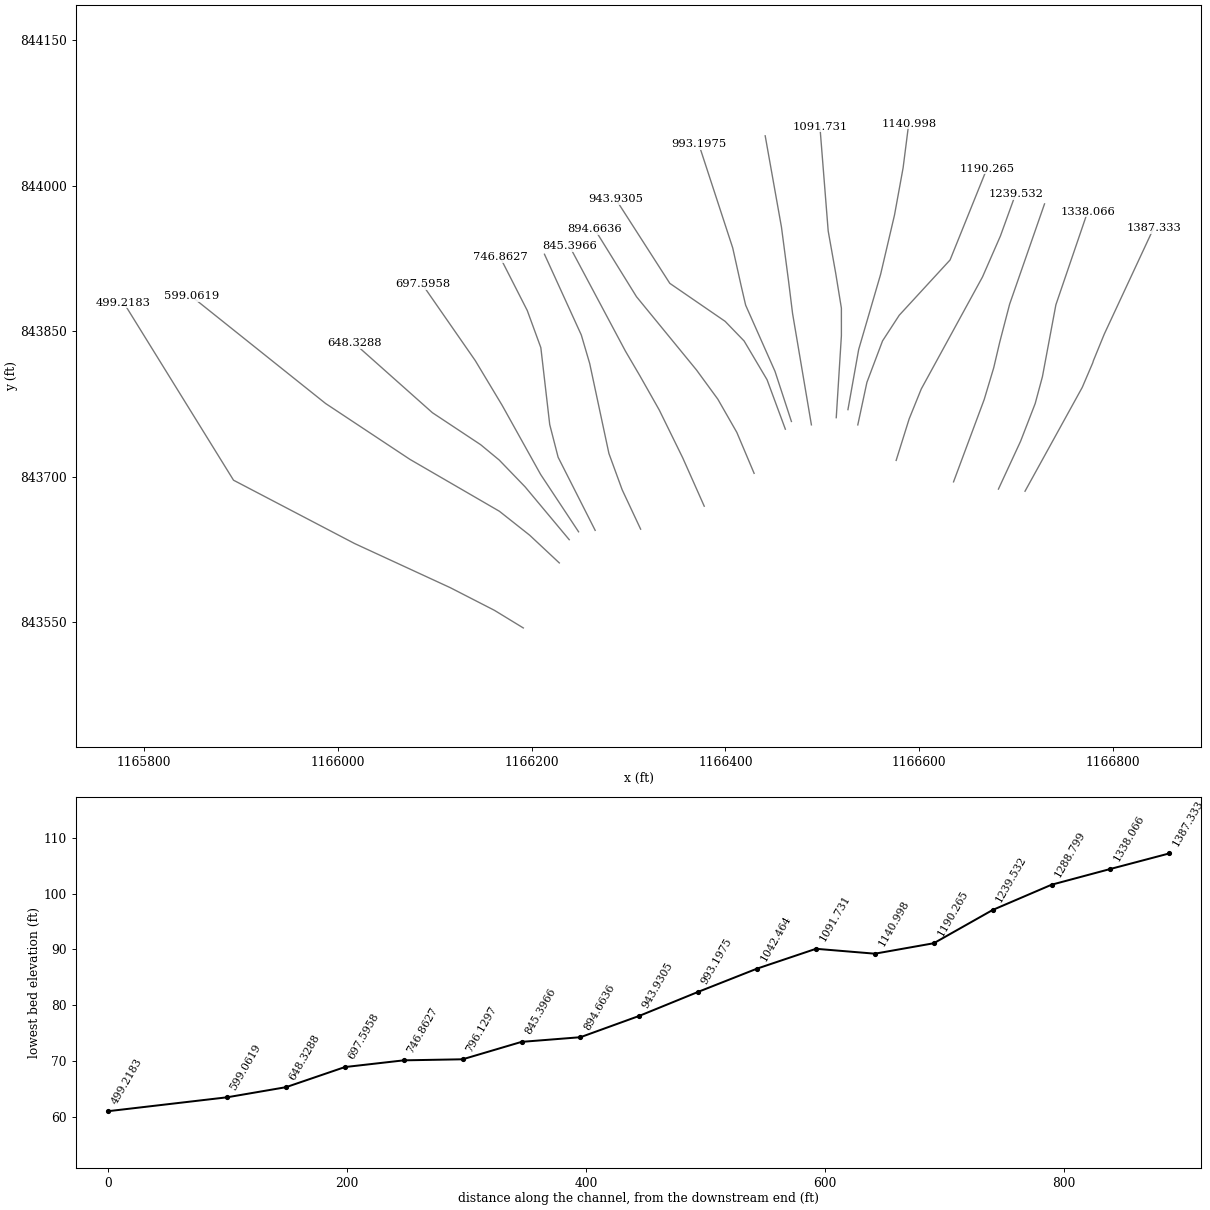
HEC-RAS study 32_ras.prj: 32

--- 32_ras.g01 (geometry) --- (continued)

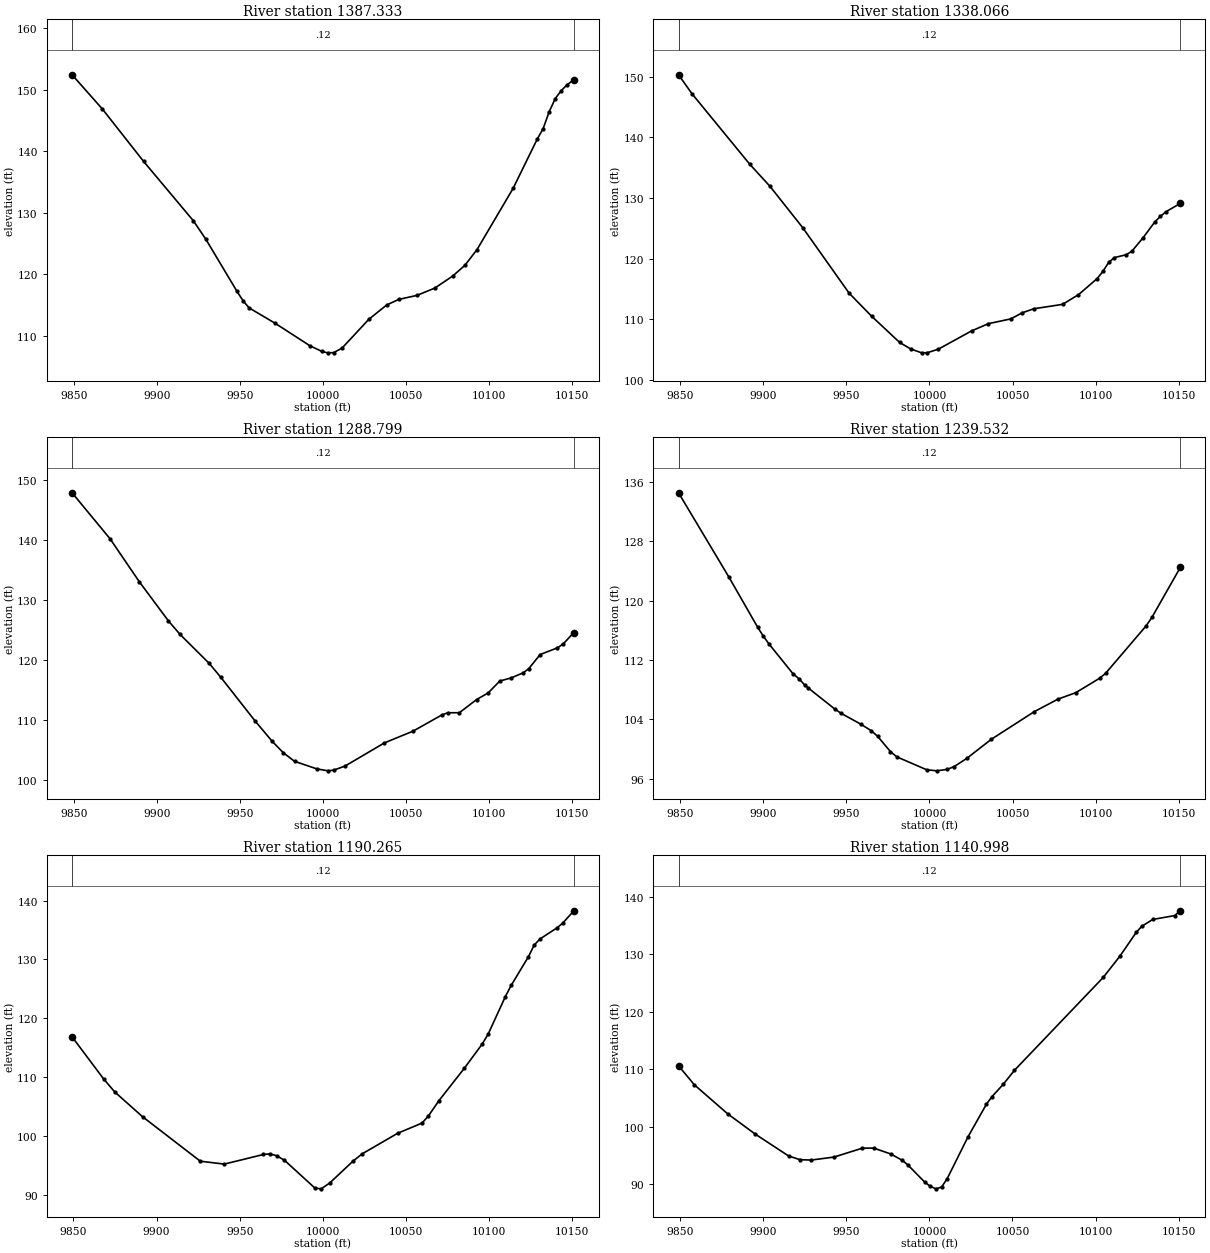
Type RM Length L Ch R = 1 ,1387.333,49.266900,49.266900,49.266900
XS GIS Cut Line= 6
1166708.98033576 843684.918488681166768.01822607843792.032192643
1166778.89416805843817.4632939361166779.44361037843819.386341815
1166790.71553655 843846.961204281166841.47458595843955.908755723
#Sta/Elev= 30
9849.035152.43519867.243146.87699892.103138.33879922.072128.67489929.564125.6756
9948.295117.20279952.041115.63799955.601114.52139971.341112.00469992.209108.3573
 9999.33 107.45210002.81107.215710006.35107.252110011.42107.965210027.62112.6731
10038.41115.010810045.65115.910310056.51116.554210067.37117.756410078.23119.7389
10085.46121.4591 10092.7 124.00410114.43133.9646 10128.9141.954910132.52143.6912
10136.14146.436310139.76148.552110143.38149.858710146.99150.825310150.98151.6181
#Mann= 3 , 0 , 0
9849.035    0.12       09849.035    0.12       010150.98    0.12       0
#XS Ineff= 2 , 0
       0                               0
Bank Sta=9849.035,10150.98
Exp/Cntr=0.3,0.1

Type RM Length L Ch R = 1 ,1338.066,49.267000,49.267000,49.267000
XS GIS Cut Line= 6
1166681.56180493843687.1200071841166704.43042983843736.522168324
1166719.45828125843775.3159139891166726.93944996843803.089441712
1166740.81503914843877.219448383  1166773.651671 843973.42635642
#Sta/Elev= 30
9849.039 150.3449857.131147.21249891.791135.60259904.075131.9181 9923.77125.0912
9951.683  114.289965.274110.45549982.083106.14269988.733105.06529995.383104.4266
9998.709104.447310005.34105.030110025.34108.046110035.44109.243410048.91110.0277
10055.83 111.04110062.77111.7028 10080.1112.431610089.69114.0329 10100.9116.6838
10104.37117.873510107.83119.3521 10111.3120.157510118.23120.6152 10121.7121.1736
10128.63123.458810135.57126.034910139.03126.9745 10142.5127.759810150.96129.1091
#Mann= 3 , 0 , 0
9849.039    0.12       09849.039    0.12       010150.96    0.12       0
#XS Ineff= 2 , 0
       0                               0
Bank Sta=9849.039,10150.96
Exp/Cntr=0.3,0.1

Type RM Length L Ch R = 1 ,1288.799,49.266900,49.266900,49.266900
XS GIS Cut Line= 6
1166635.25003339 843694.572206721166666.88011716843779.532098247
1166676.69911842843812.256862496 1166682.9003719843838.697327133
1166693.11236001843877.8652706821166729.09892526843981.282090148
#Sta/Elev= 30
9849.018147.80149871.962 140.1289889.466133.02369906.971126.52259913.972124.2758
9931.476119.47079938.478117.15739959.056 109.9159969.332 106.5369976.146104.6004
9982.891103.18029996.379101.914510003.12 101.59710006.51101.719710013.29102.3897
10037.02106.247210054.28108.200710071.65 110.90310075.13111.244710082.07 111.254
10092.49113.447710099.44114.551110106.39116.515510113.34117.051610120.28117.8605
10123.76 118.54810130.71120.925810141.13122.0389 10144.6122.690710150.98124.5844
#Mann= 3 , 0 , 0
9849.018    0.12       09849.018    0.12       010150.98    0.12       0
#XS Ineff= 2 , 0
       0                               0
Bank Sta=9849.018,10150.98
Exp/Cntr=0.3,0.1

Type RM Length L Ch R = 1 ,1239.532,49.267000,49.267000,49.267000
XS GIS Cut Line= 6
1166576.06395258843716.7072798721166589.47237621843759.527990827
1166601.97095951843790.4076254841166665.10507141843905.903987422
1166683.61754924843948.2130822491166699.23160655843991.322101623
#Sta/Elev= 30
9849.043 134.5699879.322123.21049896.588116.45669900.127115.20879903.667114.1224
9917.824110.18889921.364109.51749924.903108.66099927.227108.21659943.143105.3924
9946.807104.83219958.867103.34299965.129102.46299968.929101.70399976.56299.65648
9980.378 98.9552 9998.2697.2207510004.4197.0679810010.6997.2643210014.9197.64555
10022.4498.7419410037.25 101.32310063.02105.040110077.35106.739610088.09107.6116
10102.42109.556210105.97110.2099 10130.4116.623610133.89117.769110150.97124.5065
#Mann= 3 , 0 , 0
9849.043    0.12       09849.043    0.12       010150.97    0.12       0
#XS Ineff= 2 , 0
       0                               0
Bank Sta=9849.043,10150.97
Exp/Cntr=0.3,0.1

Type RM Length L Ch R = 1 ,1190.265,49.266900,49.266900,49.266900
XS GIS Cut Line= 6
1166536.49721785843753.3267933631166545.88671603843797.193946078
1166562.01613645843839.9637505581166579.24471262843866.437811594
1166631.67685879 843923.454619131166669.64611619844017.622067647
#Sta/Elev= 30
9849.154116.88449868.096 109.7519874.806107.53789891.582103.32169926.28495.78401
9940.71395.295169964.19996.925119968.11497.036559972.16496.713119976.882 95.9434
 9995.2191.22101    999991.0977110004.1492.1040610018.1795.8171810023.7197.05013
10044.94100.522810059.55102.248710063.29103.402610069.72106.041510085.06111.5591
 10095.8115.666610099.34117.330710109.72123.717310113.17125.595310123.55130.4548
   10127 132.42410130.46133.473410140.83135.376910144.29136.1984 10150.9138.2641
#Mann= 3 , 0 , 0
9849.154    0.12       09849.154    0.12       0 10150.9    0.12       0
#XS Ineff= 2 , 0
       0                               0
Bank Sta=9849.154,10150.9
Exp/Cntr=0.3,0.1

Type RM Length L Ch R = 1 ,1140.998,49.266900,49.266900,49.266900
XS GIS Cut Line= 6
1166526.33191404843769.0608785681166537.42457686843831.168295113
1166560.06903777 843908.76005629 1166574.3634611843969.817615287
1166583.21980389844018.3966643671166589.02923269844063.938481577
#Sta/Elev= 30
9849.059110.61389858.557107.30739878.553102.27639895.21798.732759915.29294.93439
9922.12794.291019928.96394.224839942.63394.745389959.72296.297799966.55796.30226
 9976.8195.275739983.64694.181089987.06393.370929997.24290.3805910000.5989.65103
10003.9689.2234510007.3389.53237 10010.790.9834810023.2198.2501110034.31103.9286
10037.68105.255110044.42107.381210051.17  109.8210104.58125.9595 10114.5129.6083
10124.43133.775710127.73134.832210134.35136.035710147.58136.706110150.98137.5433
#Mann= 3 , 0 , 0
9849.059    0.12       09849.059    0.12       010150.98    0.12       0
#XS Ineff= 2 , 0
       0                               0
Bank Sta=9849.059,10150.98
Exp/Cntr=0.3,0.1

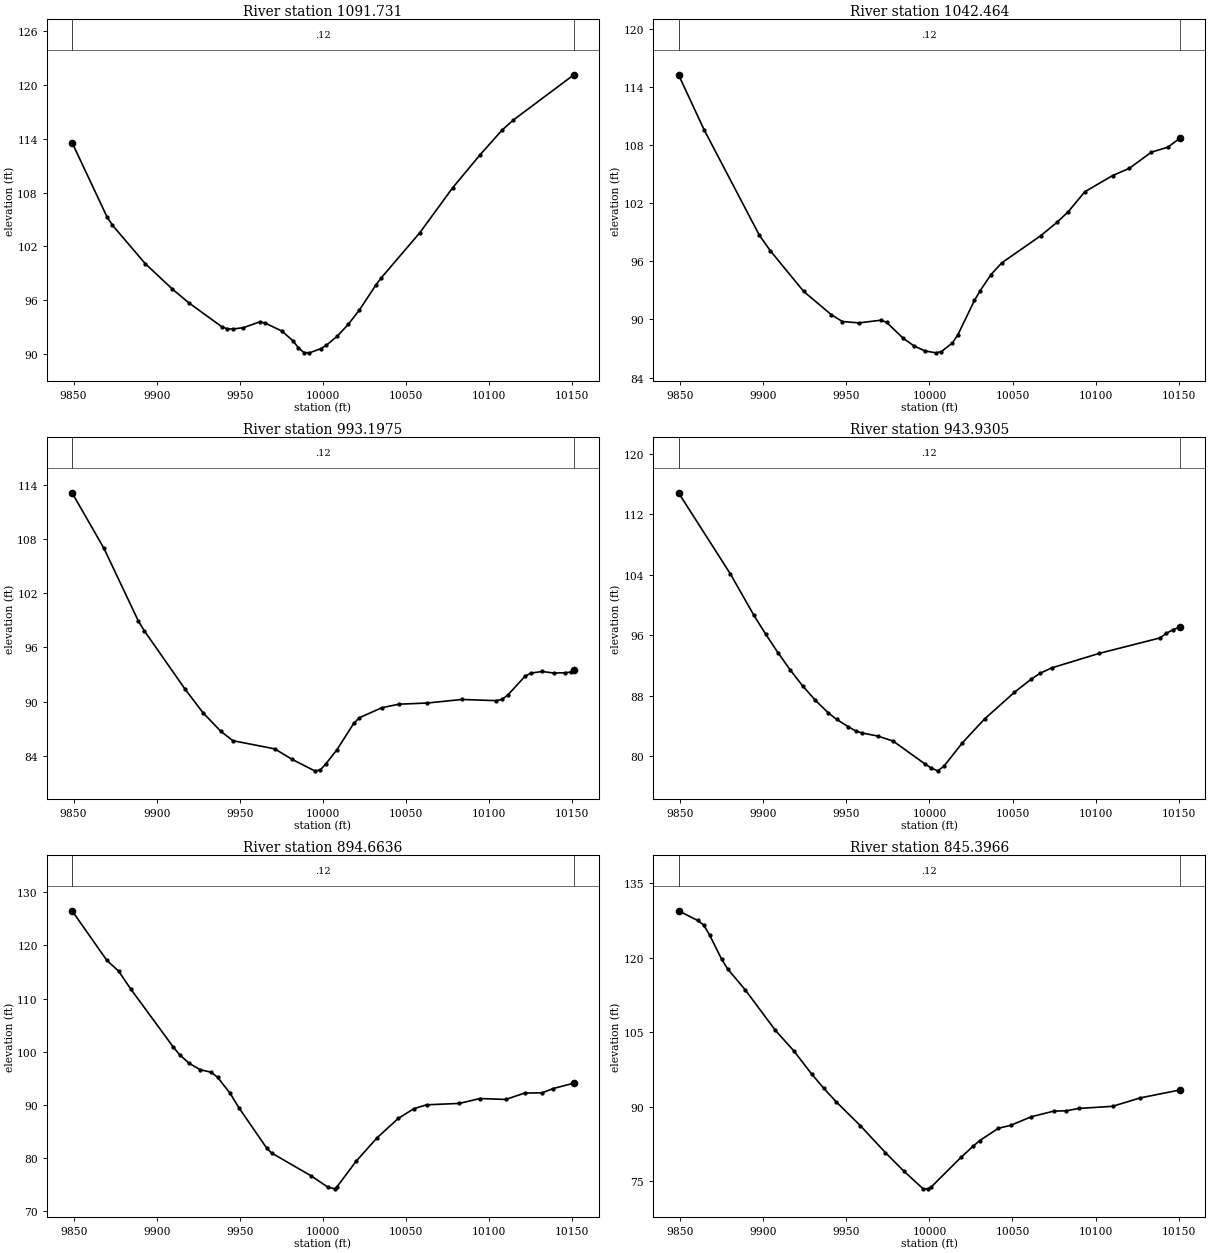
Type RM Length L Ch R = 1 ,1091.731,49.267000,49.267000,49.267000
XS GIS Cut Line= 6
1166514.27048608843760.7857589111166519.57694631843845.345440662
1166519.56859035843873.7559996191166513.65232592843910.075728967
1166505.96075152843953.3037744561166497.41809194844061.026915656
#Sta/Elev= 30
9849.065113.57549870.012105.31069873.299104.36659893.023100.07279909.45997.21041
9919.32195.686339939.03593.026079942.31692.789799945.59692.755069952.15892.91122
9962.00193.562289965.32293.417019975.29492.532049981.94291.449279985.266 90.6659
9988.59190.134599991.91590.101589998.56390.5561410001.9190.9268310008.5791.95077
10015.2393.28059 10021.994.8748710031.8997.6820410035.2298.4965110058.35103.5275
 10078.1108.540110094.55 112.21210107.72114.9582 10114.3116.056510150.97121.1442
#Mann= 3 , 0 , 0
9849.065    0.12       09849.065    0.12       010150.97    0.12       0
#XS Ineff= 2 , 0
       0                               0
Bank Sta=9849.065,10150.97
Exp/Cntr=0.3,0.1

Type RM Length L Ch R = 1 ,1042.464,49.266900,49.266900,49.266900
XS GIS Cut Line= 6
 1166488.6448903 843753.374796341166469.21625941843868.226739092
1166465.10224351843901.4639145711166464.83791613 843903.44637038
1166457.75906203 843957.325677571166440.97993631844051.490158481
#Sta/Elev= 30
9849.026115.23469864.435109.55489897.70998.664039904.36497.056979924.32992.88604
9940.96690.480979947.62189.777549957.60389.635129970.87889.913889974.18489.70633
9984.10288.066299990.71387.262149997.32586.7418710003.94 86.546510007.2586.67982
10013.8787.5752610017.1888.4261210027.1191.9586510030.4192.9234810037.0394.62065
10043.6595.8428510066.8998.6194410076.89100.028210083.56 101.11110093.56103.1705
10110.22 104.83210120.22105.578110133.55107.245210143.54107.770910150.99108.7236
#Mann= 3 , 0 , 0
9849.026    0.12       09849.026    0.12       010150.99    0.12       0
#XS Ineff= 2 , 0
       0                               0
Bank Sta=9849.026,10150.99
Exp/Cntr=0.3,0.1

Type RM Length L Ch R = 1 ,993.1975,49.267000,49.267000,49.267000
XS GIS Cut Line= 6
1166468.02163421843756.8731895061166451.09693488 843808.57245757
1166420.79240268843876.8834135191166416.10636397843897.118078528
1166407.50778719843935.7955484211166372.60375545844042.574427755
#Sta/Elev= 30
  9849.1113.0882 9868.31106.93789889.02398.907349892.47597.868329917.16291.37787
9927.92988.778369938.69786.722519945.87585.705389970.99984.803739981.54983.63563
9995.01982.376249998.38782.4677710001.7283.1325710008.4584.7082610018.5487.61401
10021.9188.2380610035.3689.3415810045.6389.7367410062.8989.86924 10083.690.25837
10104.3190.1295610107.76 90.265810111.2190.7433710121.5792.8206310125.0293.16874
10131.9293.3514910138.83 93.176610145.7393.2096310149.1893.2882610150.97 93.4916
#Mann= 3 , 0 , 0
  9849.1    0.12       0  9849.1    0.12       010150.97    0.12       0
#XS Ineff= 2 , 0
       0                               0
Bank Sta=9849.1,10150.97
Exp/Cntr=0.3,0.1

Type RM Length L Ch R = 1 ,943.9305,49.266900,49.266900,49.266900
XS GIS Cut Line= 6
1166461.77306361843748.9141475891166442.89993497843799.914591584
1166419.23817638 843839.877420711166399.67369168843860.126311156
1166342.60537354843899.3204017731166287.05587207843985.851909778
#Sta/Elev= 30
9849.156114.82599880.343104.09479894.52598.610459901.61696.118479908.94293.69378
9916.35891.392669923.77489.30397 9931.4387.390329939.30985.714299944.202 84.8768
9951.29383.883379955.85583.332369959.56383.069489969.00682.662679978.241  81.998
 9997.4678.9591210001.18 78.431310004.9578.0674910008.7378.6735410019.8781.77994
10033.18 84.928410051.1388.4512810061.3890.2045510066.5190.9615310073.6191.68358
10102.1993.5989710138.7495.64144 10142.596.2415710146.2796.6990810150.8997.10954
#Mann= 3 , 0 , 0
9849.156    0.12       09849.156    0.12       010150.89    0.12       0
#XS Ineff= 2 , 0
       0                               0
Bank Sta=9849.156,10150.89
Exp/Cntr=0.3,0.1

Type RM Length L Ch R = 1 ,894.6636,49.267000,49.267000,49.267000
XS GIS Cut Line= 6
1166429.54598606843703.3677336631166411.70029111843745.641995788
1166392.11895281843779.8716778541166370.16060406 843809.90942601
1166308.22698096843885.5443489071166265.29189777843954.907608283
#Sta/Elev= 30
9849.062126.52759869.977117.20489877.099115.16889884.222111.88059910.022100.8753
9913.80199.45019 9919.4697.854859926.06896.65426  9932.796.166949936.63795.20312
9944.06492.248279949.62489.406139966.30281.839389969.14980.972089992.74376.70513
10002.8974.5792710007.1374.2386710008.2174.5124310019.8779.3923410032.6183.85423
10045.3487.4911910054.7389.3150510062.3390.0385810082.1190.3047310094.4491.21888
10109.99  91.04910121.3892.2515510131.9492.2864310138.4793.0975810150.9794.10652
#Mann= 3 , 0 , 0
9849.062    0.12       09849.062    0.12       010150.97    0.12       0
#XS Ineff= 2 , 0
       0                               0
Bank Sta=9849.062,10150.97
Exp/Cntr=0.3,0.1

Type RM Length L Ch R = 1 ,845.3966,49.266900,49.266900,49.266900
XS GIS Cut Line= 6
1166378.11025844843669.4663766811166355.97507019843719.200984471
1166331.75453218843768.6128299251166311.79523499843803.871010189
1166296.78939069843829.4727705561166239.27772082843937.428423851
#Sta/Elev= 30
9849.018129.48769860.532127.53149864.123126.62719867.714124.60649874.896119.7535
9878.487117.78939889.261113.49579907.282105.38119918.243101.29159929.20596.53426
9936.51293.64951 9943.8290.982269958.43586.144929973.51380.711589984.82476.90541
9996.134 73.4382    999973.40083   1000173.7474410018.9479.7332710026.5382.07063
 10030.3 83.134210041.4585.6087610048.8886.2079810061.3787.9486910074.9189.08358
10082.3489.1380210089.7889.6123410110.2190.0470110126.9591.75352   1015193.35963
#Mann= 3 , 0 , 0
9849.018    0.12       09849.018    0.12       0   10151    0.12       0
#XS Ineff= 2 , 0
       0                               0
Bank Sta=9849.018,10151
Exp/Cntr=0.3,0.1

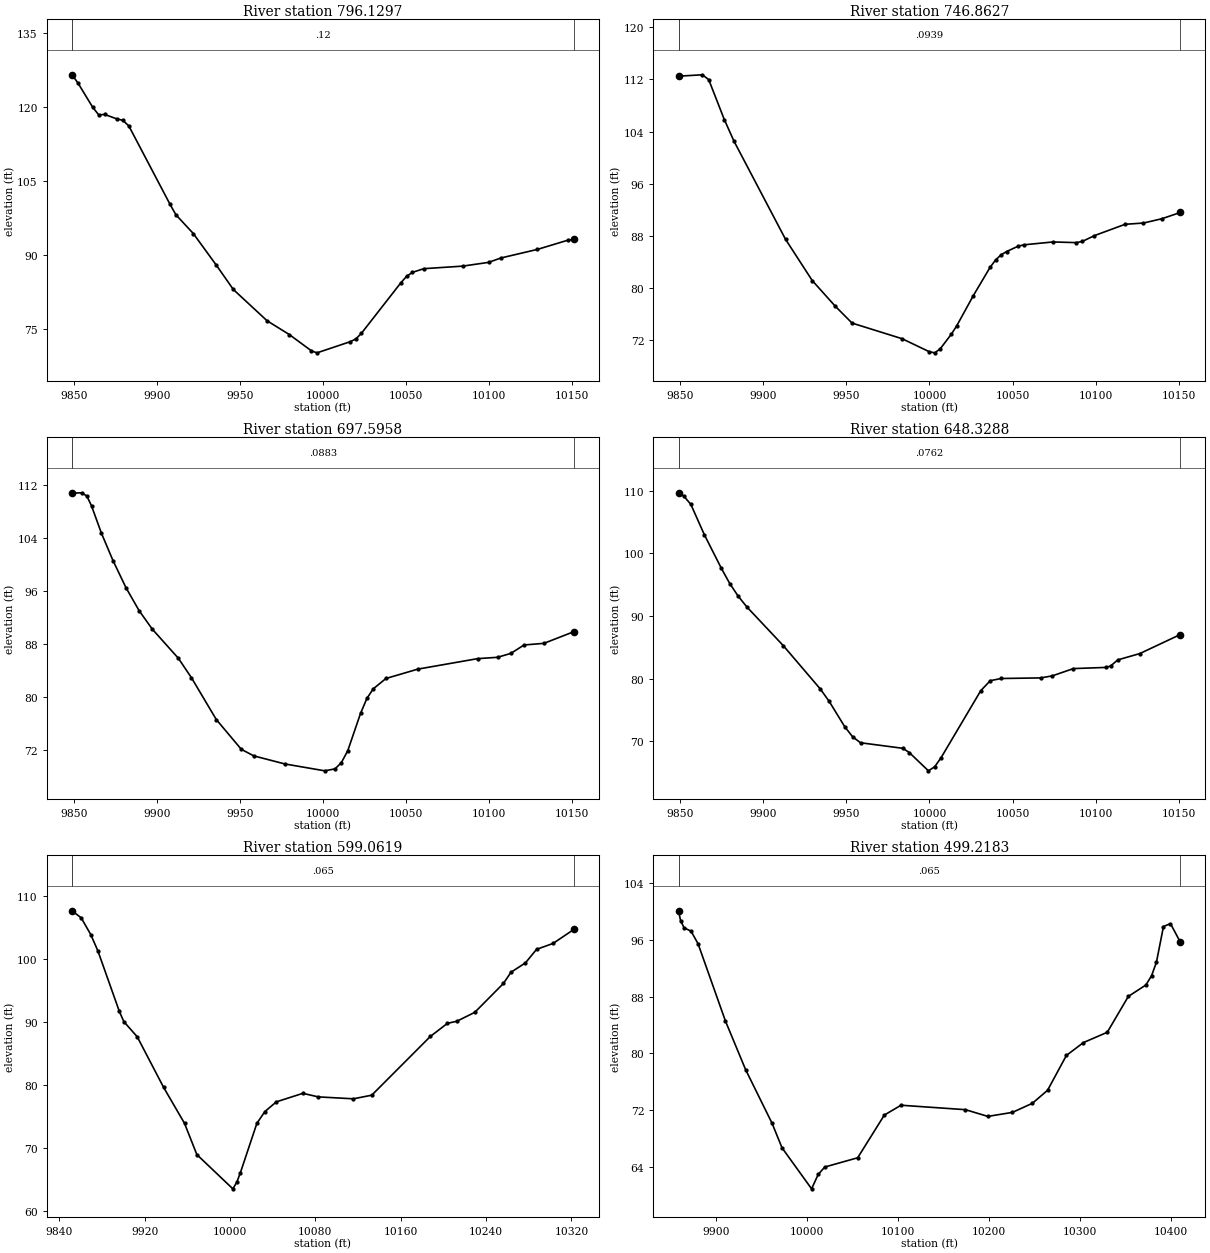
Type RM Length L Ch R = 1 ,796.1297,49.267000,49.267000,49.267000
XS GIS Cut Line= 6
 1166312.5042898843645.7892601221166293.45008146843686.417326057
1166279.79067543843723.8332324331166259.96588937843816.624488292
1166251.32519335843846.0120262831166213.31515017843929.345486284
#Sta/Elev= 30
9849.039126.46169852.708124.72889861.443119.89839865.067118.36429868.691118.4463
9875.938117.54929879.562117.26279883.186116.12749908.022100.25989911.515 98.1763
9921.99394.380619935.89887.965079946.06783.078369966.39176.751929979.73673.97607
9993.08270.677449996.41870.2768610016.4872.5368210019.8273.0903110023.1774.23773
10046.9884.48072 10050.485.7585910053.8286.5404810060.7187.2845210084.0187.79578
 10099.788.5592910107.0289.4395210128.9891.1725510147.2893.0312810150.9693.20306
#Mann= 3 , 0 , 0
9849.039    0.12       09849.039    0.12       010150.96    0.12       0
#XS Ineff= 2 , 0
       0                               0
Bank Sta=9849.039,10150.96
Exp/Cntr=0.3,0.1

Type RM Length L Ch R = 1 ,746.8627,49.266900,49.266900,49.266900
XS GIS Cut Line= 6
1166265.61024753843644.5481788711166227.39405918843719.973778124
1166218.73699069843753.6549789341166209.56622101843833.010990486
1166195.58452043843871.2522766061166167.63887556843926.109075145
#Sta/Elev= 30
9849.118112.48349863.503112.69779867.288111.94169876.646105.83549882.425102.5429
9913.48187.480619929.55581.15648 9943.3377.245729953.49274.643899983.53772.25447
9999.98570.2514710003.2770.0873310006.5670.7216210013.13 72.923310016.4274.22128
 10026.478.8498310036.4483.1681710039.7884.3132310043.13 85.108810046.4785.61671
10053.3786.4291910056.8686.6394310074.3387.08067 10088.386.9767110091.9387.15627
10099.2988.05539 10117.789.7853710128.7589.9773910139.79 90.637710150.9191.59476
#Mann= 3 , 0 , 0
9849.118  0.0939       09849.118  0.0939       010150.91  0.0939       0
#XS Ineff= 2 , 0
       0                               0
Bank Sta=9849.118,10150.91
Exp/Cntr=0.3,0.1

Type RM Length L Ch R = 1 ,697.5958,49.267000,49.267000,49.267000
XS GIS Cut Line= 6
1166248.50261919843643.0615177061166209.31427671843702.274601587
1166170.90952872843771.2721984691166169.27478372843774.147467954
1166141.97276453843819.5821889951166087.42398783843898.163099741
#Sta/Elev= 30
9849.028110.82069854.777 110.8819857.898 110.3959860.722108.91129866.666 104.789
9873.635100.65159881.50396.528179889.37293.077349897.24190.302379912.97885.88662
9920.80982.967379935.82876.623959950.84872.138079958.35771.141149977.13169.91934
10001.1168.8814310007.2869.1818810011.1170.1315410014.94 71.938110022.5977.54428
10026.4279.8153410030.2581.26315 10037.982.8312910057.1284.2467110093.0685.82762
10105.0486.0294710113.0386.6200810121.0287.8920710132.9788.1391710150.9789.90071
#Mann= 3 , 0 , 0
9849.028  0.0883       09849.028  0.0883       010150.97  0.0883       0
#XS Ineff= 2 , 0
       0                               0
Bank Sta=9849.028,10150.97
Exp/Cntr=0.3,0.1

Type RM Length L Ch R = 1 ,648.3288,49.266900,49.266900,49.266900
XS GIS Cut Line= 6
1166238.84584917843634.932571176 1166193.3175572843689.441295562
1166166.62275927843717.0894895111166147.44413004843732.948096304
1166097.74308976843765.8800468721166017.12865874843837.566353108
#Sta/Elev= 30
9849.048109.68429852.178109.16659856.453 107.8329864.523103.01739874.75997.64585
9879.87795.184789884.99593.148019890.11391.464269912.02485.283389934.28978.36475
9939.65676.382169949.10272.294899953.82670.702979958.54469.75649 9984.0268.87037
9987.86968.199019999.40365.2715710003.1865.9288910007.0167.3709610030.8878.07018
10036.5979.6688110043.1580.0205910066.8880.1136510073.8880.4364110086.6381.60587
10106.3781.7908310109.01 82.0256 10113.483.0002710126.5784.0003510150.96 87.0472
#Mann= 3 , 0 , 0
9849.048  0.0762       09849.048  0.0762       010150.96  0.0762       0
#XS Ineff= 2 , 0
       0                               0
Bank Sta=9849.048,10150.96
Exp/Cntr=0.3,0.1

Type RM Length L Ch R = 1 ,599.0619,99.843600,99.843600,99.843600
XS GIS Cut Line= 6
1166228.61429112843610.9527095641166198.03663741843639.563146512
1166166.78822954843664.2631762641166074.51622667843717.786306052
1165987.54713192843775.4041111091165848.92406292843886.141764362
#Sta/Elev= 30
9852.036107.58789860.596106.46179869.582103.80459876.245101.21469896.35991.60957
9900.54190.000539913.08787.590929937.88379.542539957.40273.856139968.973 68.8915
10002.7263.4574510006.4764.5232110009.8466.0498110025.2273.8516410032.7275.71936
10043.4477.2612210068.3378.6156110082.6978.0516310115.6877.7457610132.8878.32164
10187.89 87.658210203.7989.7202310212.6790.0597510229.4291.4681510256.2596.04912
10263.3797.8331610276.9499.3238410287.28101.4611 10302.8102.405610322.28104.6288
#Mann= 3 , 0 , 0
9852.036   0.065       09852.036   0.065       010322.28   0.065       0
#XS Ineff= 2 , 0
       0                               0
Bank Sta=9852.036,10322.28
Exp/Cntr=0.3,0.1

Type RM Length L Ch R = 1 ,499.2183,99.843700,99.843700,99.843700
XS GIS Cut Line= 6
1166191.47778174843543.8881636561166161.76251355843562.025509685
1166116.23769498 843585.384669141166017.42162919843630.978479058
 1165892.5803358843696.284294605 1165779.2243751843879.468046188
#Sta/Elev= 30
9859.079100.05579861.33198.684699865.17597.664489872.86397.18327 9880.5595.40852
9910.59284.554269932.71777.730369961.87570.154089972.71766.7312110005.2360.95609
10012.4662.9770410019.6964.0232710055.84  65.32510085.1471.3309410103.4572.71298
10174.1872.0877510198.7971.14234 10225.871.7064810247.6972.9811110264.3874.80998
 10285.179.71588 10303.881.5235410329.9782.9679210353.1288.0123810372.41 89.6218
10378.6290.9165810383.9892.82014 10391.797.8423910399.4198.2497210410.2395.64895
#Mann= 3 , 0 , 0
9859.079   0.065       09859.079   0.065       010410.23   0.065       0
#XS Ineff= 2 , 0
       0                 10111.8       0
Bank Sta=9859.079,10410.23
Exp/Cntr=0.3,0.1