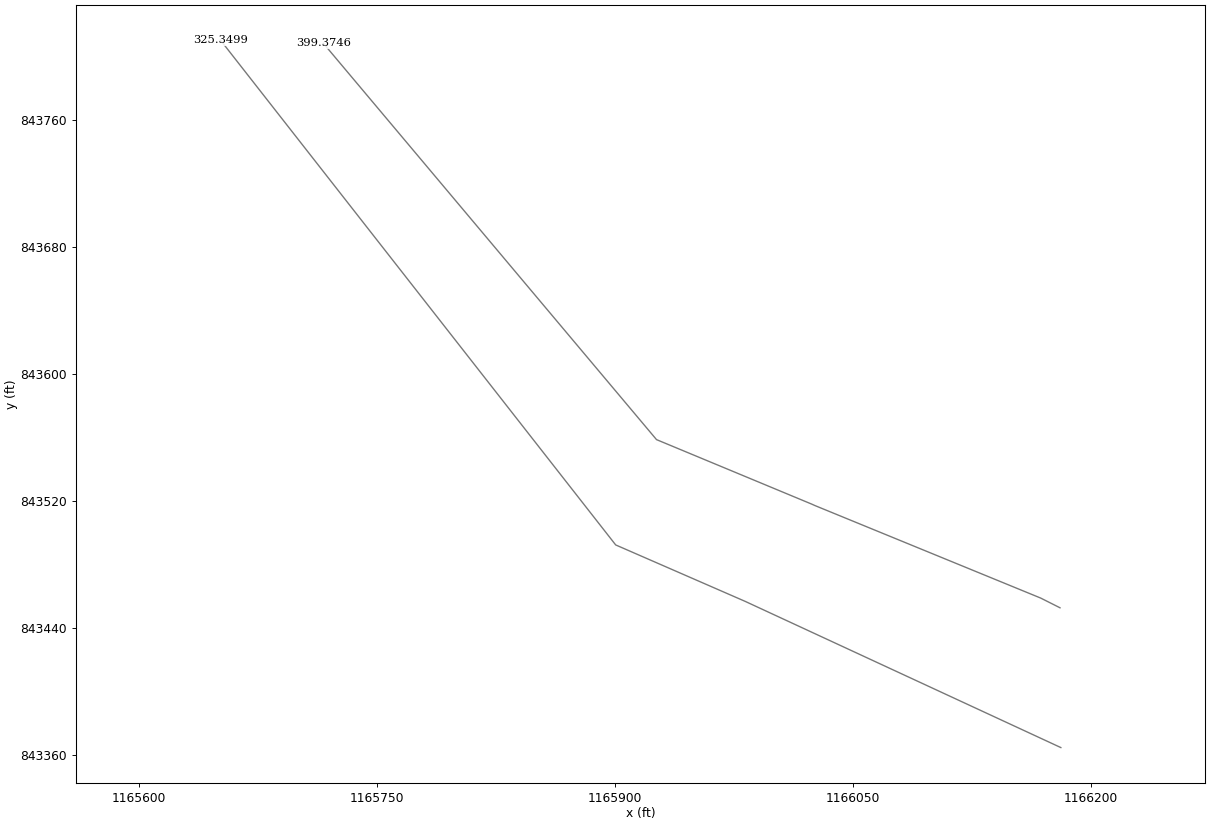
HEC-RAS study 32_ras.prj: 32

--- 32_ras.g01 (geometry) --- (continued)

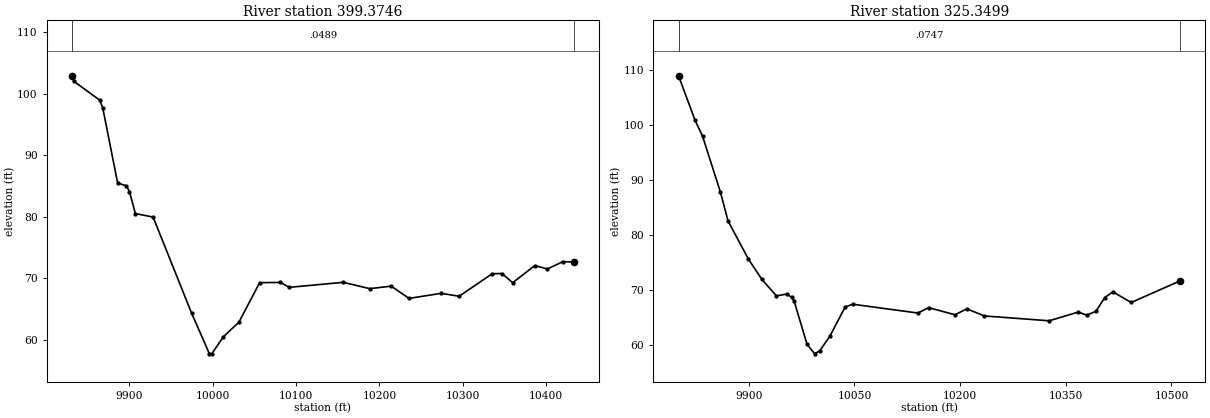
Type RM Length L Ch R = 1 ,399.3746,74.024700,74.024700,74.024700
XS GIS Cut Line= 6
 1166180.6095728843452.595208406 1166168.4220835843458.727782264
1166026.03245151843517.0746566361166024.21116108843517.901034981
1165926.36414009843558.5636049511165716.42527062843808.295727789
#Sta/Elev= 30
9831.476102.9361 9833.73102.02859864.82898.952019868.37397.637129886.10185.49867
9896.73885.008769900.284 84.09829907.37580.508419928.64979.940159974.74164.32158
9996.01557.73457    999957.67962   1001360.4697810031.5762.8390210056.4469.26473
10081.3169.3005510091.9668.5049510156.82 69.319910188.4468.2855710214.1568.69894
10235.5866.6992710274.1667.5297910295.5967.0484910335.2770.7184210347.0270.75503
10359.8869.2540410386.2572.0367910401.5571.5002210419.8972.6754410433.2172.64528
#Mann= 3 , 0 , 0
9831.476  0.0489       09831.476  0.0489       010433.21  0.0489       0
#XS Ineff= 2 , 0
       0                10092.17       0
Bank Sta=9831.476,10433.21
Exp/Cntr=0.3,0.1

Type RM Length L Ch R = 1 ,325.3499,0.000000,0.000000,0.000000
XS GIS Cut Line= 4
1166181.13864362843364.5153896211165982.27481285843456.620742828
1165900.63597703843492.2069020121165651.53286269843810.389031306
#Sta/Elev= 30
9800.254108.89859823.519100.87619834.366 97.91529859.67687.779689870.52382.52062
9899.44875.588939918.56771.90408 9939.2268.911299953.68369.231319960.91468.66131
 9964.5367.891079982.60860.133799993.45558.3784410000.6958.9311810015.1561.60188
10036.67 66.8685 10047.467.3932610140.0765.7922710155.2866.7743610192.78 65.4783
10209.4566.5543110234.4565.2623710326.3464.3843510367.7865.9706410379.5765.40587
10392.7866.1108610405.28 68.602410416.82 69.639910442.7967.7079210512.56 71.6516
#Mann= 3 , 0 , 0
9800.254  0.0747       09800.254  0.0747       010512.56  0.0747       0
#XS Ineff= 2 , 0
       0                10079.94       0
Bank Sta=9800.254,10512.56
Exp/Cntr=0.3,0.1